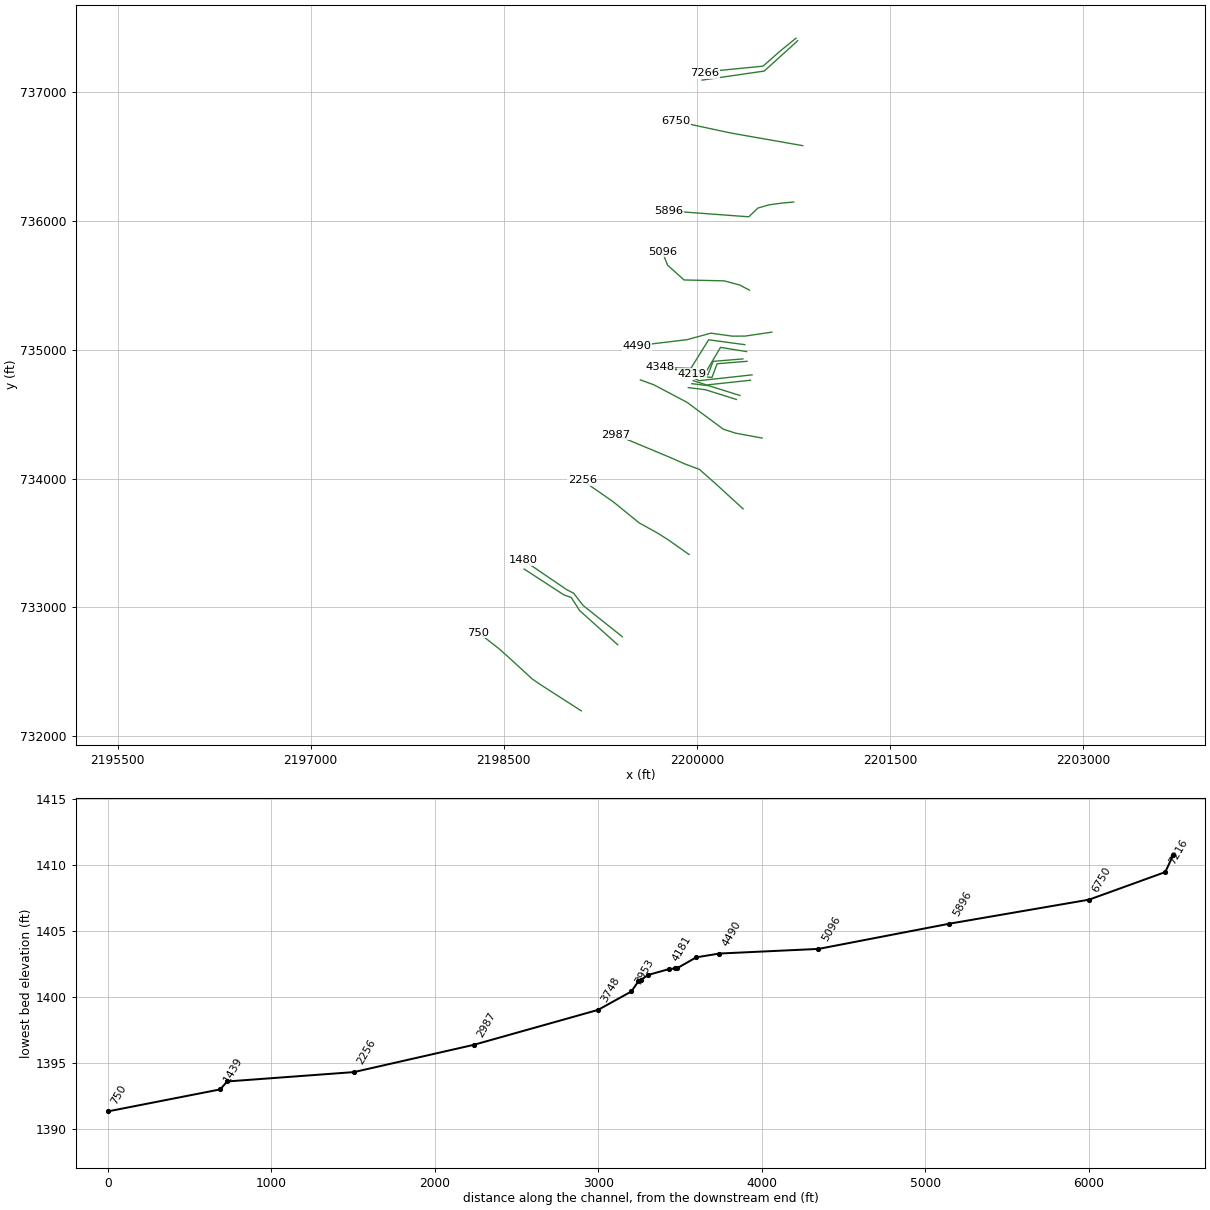
HEC-RAS study BRUSHRN2.prj: BRUSHRN2

--- BRUSHRN2.g01 (geometry) --- (continued)

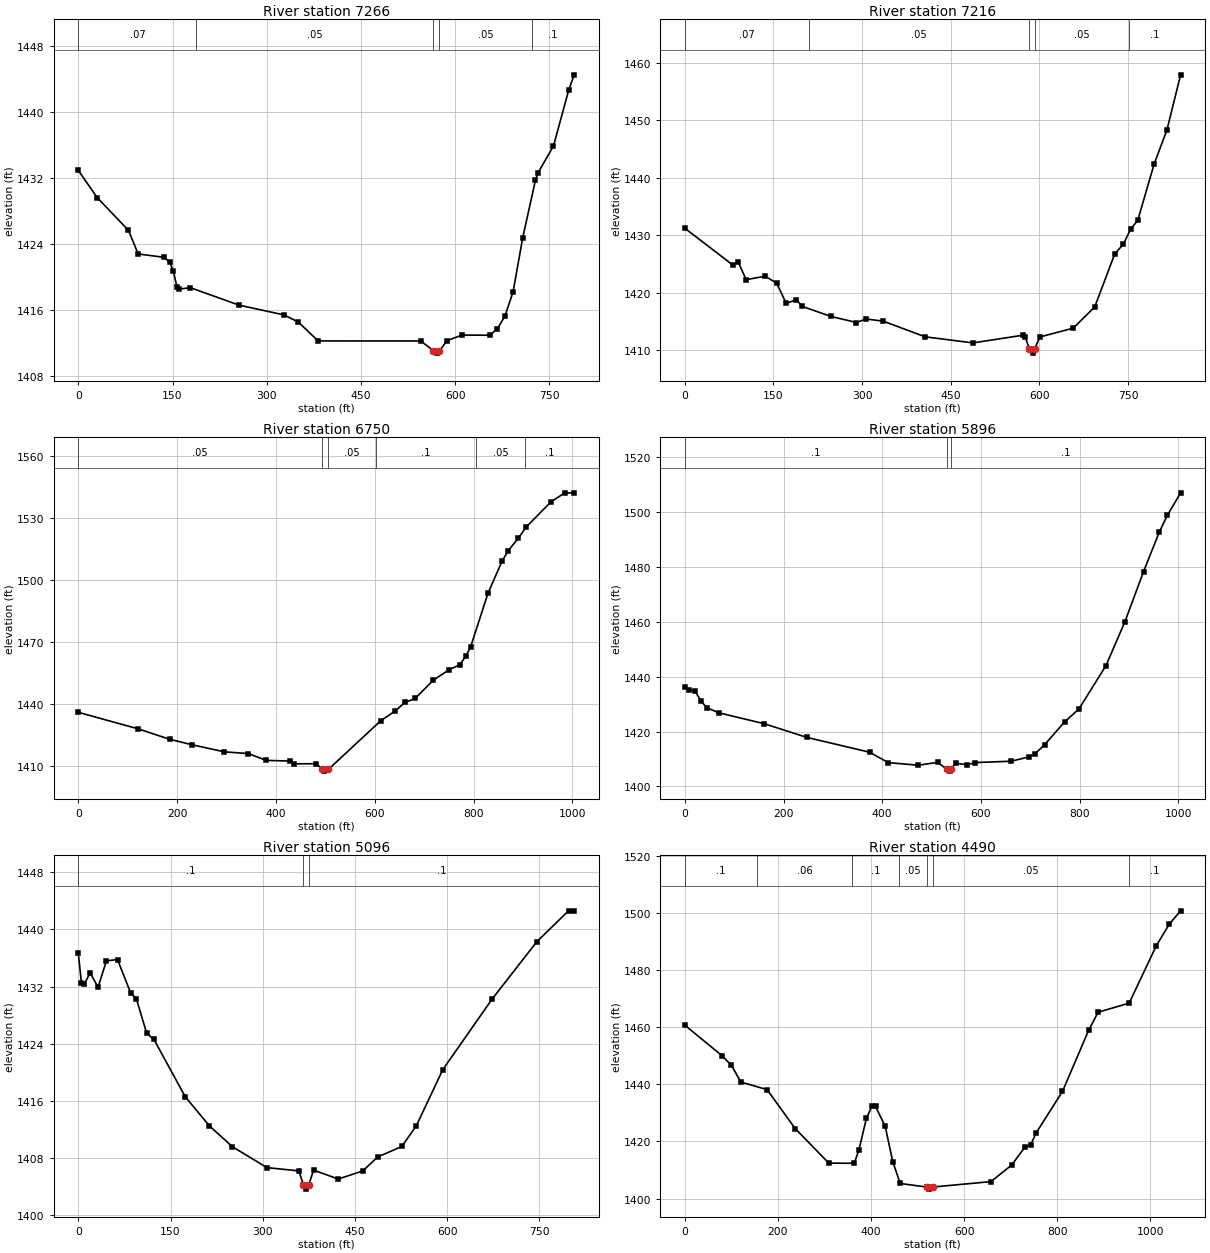
Type RM Length L Ch R = 1 ,7266    ,50,50,50
XS GIS Cut Line= 5
2200770.12570582737420.1003979892200647.51801924737320.481652639
2200514.17778123737203.1106169792200159.29529502737168.204142926
2200063.91012259737149.302933643
#Sta/Elev= 30
       0 1432.94      30 1429.65    79.8 1425.68    95.3 1422.82   136.5 1422.41
   145.6 1421.84   151.3 1420.73   157.1  1418.8   159.9 1418.56   178.4 1418.73
   256.2 1416.61   327.6 1415.43   350.2 1414.57   381.8 1412.28   545.2 1412.27
   565.5  1411.1   570.7  1410.8   574.71411.025   586.8  1412.3   610.9 1412.99
   655.2 1412.97   667.2 1413.74   679.3  1415.3   692.2 1418.21   707.6 1424.79
   727.9 1431.77   732.1 1432.67   756.6 1435.91     781 1442.73   789.5 1444.53
#Mann= 5 ,-1,0
       0     .07       0  187.98     .05       0   565.5    .045       0
   574.7     .05       0  722.21      .1       0
Bank Sta=565.5,574.7
XS Rating Curve= 0 ,0
Exp/Cntr(USF)=0,0
Exp/Cntr=0.3,0.1

Type RM Length L Ch R = 1 ,7216    ,466.3,466.3,466.3
XS GIS Cut Line= 3
2200783.37144239737400.4522813782200523.49591675737165.035628734
2200040.43317495737094.716368853
#Sta/Elev= 30
       0 1431.21      81 1424.83    90.7 1425.29   103.7 1422.26     136 1422.86
   155.4 1421.66   171.6 1418.12   188.7 1418.77   198.6 1417.61   247.2 1415.86
   290.4  1414.8   306.6 1415.42   335.9 1415.03   406.6 1412.31   487.4 1411.25
   572.3 1412.59   576.3  1412.2   582.8  1410.2   588.5 1409.47   591.8  1410.2
   600.6 1412.28   657.2 1413.82   693.5 1417.52   727.5 1426.78   742.1 1428.45
   754.2 1431.06   766.3 1432.59   793.9 1442.36   815.7 1448.35   838.8 1457.92
#Mann= 5 ,-1,0
       0     .07       0     210     .05       0   582.8    .045       0
   591.8     .05       0  750.65      .1       0
Bank Sta=582.8,591.8
XS Rating Curve= 0 ,0
Exp/Cntr(USF)=0,0
Exp/Cntr=0.3,0.1

Type RM Length L Ch R = 1 ,6750    ,853.8,853.8,853.8
XS GIS Cut Line= 6
2200822.80036493736585.6817454252200279.54390551736681.041790918
2200206.04077168736696.1037686772200120.42545734736714.460687339
2199933.86086984736754.6807512492199837.54446143736775.675131842
#Sta/Elev= 30
       0 1435.89   120.4 1427.93   184.9 1422.82   230.1 1420.18   295.5 1416.73
   343.9  1415.9   380.4 1412.59   429.1 1412.26   437.2 1410.91   481.9 1410.97
   493.61408.254   498.1 1407.38     5061408.201   612.1 1431.81   640.8 1436.47
   661.2 1440.68   681.7 1442.61   718.5 1451.48   751.2 1456.64   771.7 1458.91
     784    1463   794.1 1467.65     829 1493.55   857.6 1509.18   869.9 1514.23
   890.4 1520.27   906.7  1525.8   956.3 1537.87   984.5 1542.34  1003.6 1542.28
#Mann= 6 ,-1,0
       0     .05       0   493.6    .045       0     506     .05       0
  601.56      .1       0  804.15     .05       0     905      .1       0
Bank Sta=493.6,506
XS Rating Curve= 0 ,0
Exp/Cntr(USF)=0,0
Exp/Cntr=0.3,0.1

Type RM Length L Ch R = 1 ,5896    ,800.1,800.1,800.1
XS GIS Cut Line= 6
2200752.24649385 736148.047292382200660.73754681736139.582472521
2200560.72686771736126.0675158862200474.93804506736101.251406573
2200403.28151751736033.0936500962199781.29563768736079.218035713
#Sta/Elev= 30
       0 1436.11     8.1 1434.98    20.2 1434.94    32.2 1431.26    44.3  1428.7
    68.4 1426.84   161.1 1422.83   247.5 1417.84   374.3 1412.46   412.2 1408.67
   472.4 1407.71   512.5 1408.75   530.71406.286   536.5 1405.56  539.46 1406.29
   548.6 1408.41   572.6 1407.93   588.7 1408.69   660.9 1409.16     697 1410.73
     709 1411.77   729.1 1415.18   769.4 1423.46   798.8 1428.25   853.4 1444.01
     892 1460.08   929.6  1478.3   961.7 1492.77   977.7 1498.77  1004.7 1506.98
#Mann= 3 ,-1,0
       0      .1       0   530.7    .045       0  539.46      .1       0
Bank Sta=530.7,539.46
XS Rating Curve= 0 ,0
Exp/Cntr(USF)=0,0
Exp/Cntr=0.3,0.1

Type RM Length L Ch R = 1 ,5096    ,606.3,606.3,606.3
XS GIS Cut Line= 6
2200408.55705534735463.6094246152200333.38275513735503.140337302
2200211.99399494735535.7158355182199900.71894293735542.545539091
2199772.54876473735657.6953176412199731.29290464735761.764094267
#Sta/Elev= 30
       0 1436.65       5 1432.55     9.5  1432.3    19.2 1433.94    32.1 1431.89
    45.6  1435.6    63.7 1435.78    84.9 1431.15    94.5 1430.26   111.2 1425.45
   122.9 1424.61   173.8 1416.59   213.3 1412.49   250.7 1409.58   306.7 1406.66
   358.7  1406.2     366 1404.27   370.7 1403.65   374.7 1404.26   382.7 1406.31
   422.7 1405.06   462.7  1406.2   486.7 1408.14   526.1 1409.62   549.9 1412.55
   592.8 1420.38   673.5 1430.31   745.6 1438.27   797.2  1442.6   806.4 1442.55
#Mann= 3 ,-1,0
       0      .1       0     366    .045       0   374.7      .1       0
Bank Sta=366,374.7
XS Rating Curve= 0 ,0
Exp/Cntr(USF)=0,0
Exp/Cntr=0.3,0.1

Type RM Length L Ch R = 1 ,4490    ,141.5,141.5,141.5
XS GIS Cut Line= 6
2200582.87531984735137.3175161782200375.76746634735106.782472253
2200275.96550059 735106.201108592200108.56918184735129.409395501
2199924.53871001735078.9124492562199531.91777609 735031.72422342
#Sta/Elev= 30
       0 1460.66    79.9 1449.97   100.2 1446.57   120.3 1440.76   176.8  1438.1
     237 1424.49   309.2  1412.4   363.8 1412.34   373.9 1417.02   390.1 1428.17
   402.2 1432.37   409.5 1432.27   430.4 1425.22   446.5 1412.95   462.6 1405.27
   519.21404.035   524.8  1403.3     533 1404.04   657.3 1405.93     702 1411.73
     731 1418.16   742.4 1418.65   754.5    1423     811 1437.47     867  1458.8
   887.5 1465.18   954.2 1468.36    1012 1488.29  1040.3    1496  1064.7 1500.65
#Mann= 7 ,-1,0
       0      .1       0  155.22     .06       0  359.22      .1       0
  459.63     .05       0   519.2    .045       0     533     .05       0
  953.34      .1       0
Bank Sta=519.2,533
XS Rating Curve= 0 ,0
Exp/Cntr(USF)=0,0
Exp/Cntr=0.3,0.1

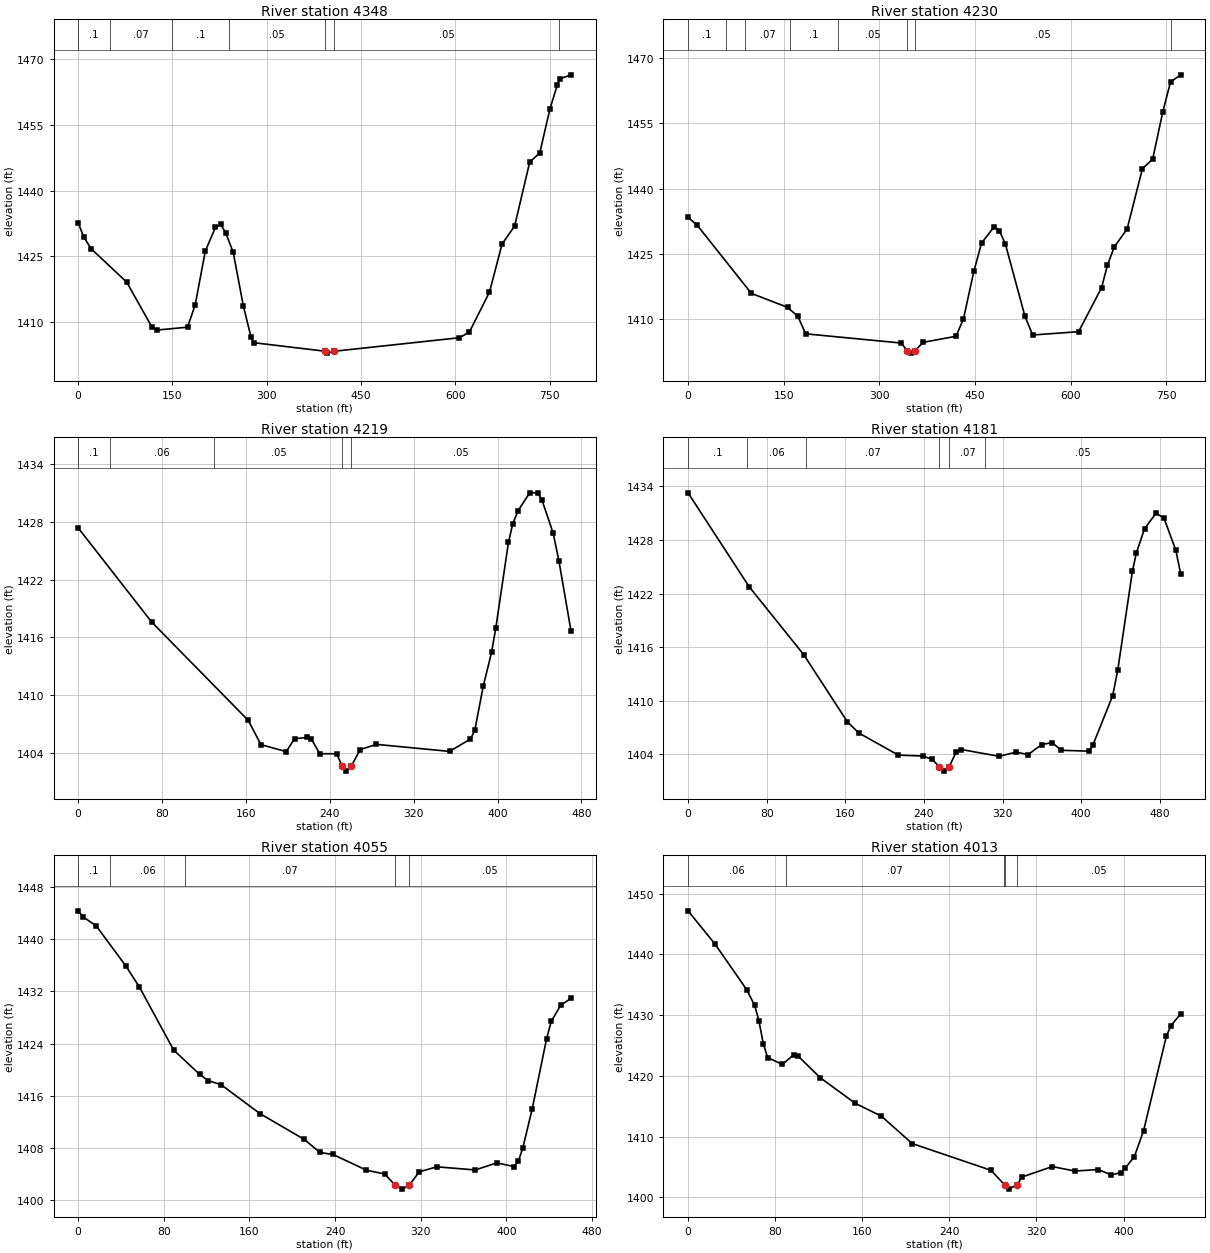
Type RM Length L Ch R = 1 ,4348    ,118.6,118.6,118.6
XS GIS Cut Line= 4
2200372.65112849735040.0380577412200091.92076006735077.950197529
2199953.41106417734855.7930821082199714.60470218734864.017408729
#Sta/Elev= 30
       0 1432.68     8.6  1429.5    20.7 1426.74    77.2 1419.16   117.5  1408.9
   125.6 1408.26     174 1408.91   186.2 1414.02   202.3 1426.23   218.4 1431.61
   226.5 1432.32   234.6 1430.44   246.7 1425.93   262.8 1413.73   274.9 1406.72
     279 1405.39     3921403.456   396.2 1403.01   407.71403.443   606.4 1406.51
   622.4 1407.79   654.4 1416.88   674.4 1427.82   694.4 1431.91   718.4 1446.46
   734.4 1448.53   750.4 1458.45   762.4 1464.04   766.4  1465.4     784 1466.31
#Mann= 7 ,-1,0
       0      .1       0      50     .07       0     150      .1       0
     240     .05       0     392    .045       0   407.7     .05       0
  765.08      .1       0
Bank Sta=392,407.7
XS Rating Curve= 0 ,0
Exp/Cntr(USF)=0,0
Exp/Cntr=0.3,0.1

Type RM Length L Ch R = 1 ,4230    ,10.8,10.8,10.8
XS GIS Cut Line= 4
2200386.19117841734986.3291930432200183.99309955735018.925609527
2200075.57240349734836.8871605482199720.12101881734850.828397136
#Sta/Elev= 30
       0  1433.4    14.2 1431.62    99.3 1415.91     156  1412.7   172.2 1410.63
   184.4 1406.61   334.3 1404.49   343.51402.734   348.9 1402.17   355.8 1402.72
   368.6 1404.65   420.1 1406.05   431.8 1410.07   448.1 1421.02   460.1 1427.49
   480.1 1431.27   488.1 1430.32   497.3 1427.34   528.1 1410.67   540.2 1406.34
   612.2  1407.1   648.3 1417.23   657.4 1422.41   668.3 1426.63   688.3 1430.72
   712.3 1444.61   728.3 1446.78   744.3 1457.71   756.3 1464.55   772.4 1466.18
#Mann= 8 ,-1,0
       0      .1       0      60     .06       0      90     .07       0
     160      .1       0  234.81     .05       0   343.5    .045       0
   355.8     .05       0  756.69      .1       0
Bank Sta=343.5,355.8
XS Rating Curve= 0 ,0
Exp/Cntr(USF)=0,0
Exp/Cntr=0.3,0.1

Type RM Length L Ch R = 1 ,4219    ,37.4,37.4,37.4
XS GIS Cut Line= 4
2200357.90751857734929.4108350292200126.22221987734910.354468469
2200086.10355343734806.045935721 2199960.7327208734816.075602331
#Sta/Elev= 30
       0 1427.34      70 1417.61   162.3 1407.41   174.3 1404.91   198.4 1404.19
   206.4 1405.52   218.5 1405.66   222.5 1405.47   230.5 1403.97   246.6 1403.97
   251.8 1402.68   255.2 1402.17   260.61402.701     269  1404.4   284.5 1404.94
   354.2 1404.21   374.2 1405.49   378.3 1406.39   386.3 1410.93   394.3 1414.47
   398.3 1416.95   410.4 1425.84   414.4 1427.72   419.5 1429.11   430.7 1430.97
   438.5 1430.97   442.5 1430.19     453 1426.81   458.5 1423.96     470 1416.72
#Mann= 5 ,-1,0
       0      .1       0      30     .06       0     130     .05       0
   251.8    .045       0   260.6     .05       0
Bank Sta=251.8,260.6
XS Rating Curve= 0 ,0
Exp/Cntr(USF)=0,0
Exp/Cntr=0.3,0.1

Type RM Length L Ch R = 1 ,4181    ,126.1,126.1,126.1
XS GIS Cut Line= 4
2200389.50096839734910.8559517992200157.81566969 734891.79958524
2200117.69700325734785.4851191692199963.24013745734800.529619085
#Sta/Elev= 30
       0 1433.28    62.1 1422.78   117.7 1415.16   162.2 1407.63   173.9 1406.38
     214 1403.91   238.9 1403.81   248.1 1403.45   255.61402.632   260.9 1402.12
   265.81402.637     273  1404.3     278 1404.54   316.5 1403.78   333.6 1404.24
   346.1 1403.98   359.7 1405.09   370.4 1405.31   379.8 1404.45   407.9 1404.36
   411.9 1405.04     432 1410.56   437.2 1413.44   452.1 1424.51   456.1 1426.54
   464.4 1429.26   476.2 1431.01   484.3 1430.43   496.3 1426.83   501.3 1424.16
#Mann= 6 ,-1,0
       0      .1       0      60     .06       0     120     .07       0
   255.6    .045       0   265.8     .07       0  302.47     .05       0
Bank Sta=255.6,265.8
XS Rating Curve= 0 ,0
Exp/Cntr(USF)=0,0
Exp/Cntr=0.3,0.1

Type RM Length L Ch R = 1 ,4055    ,42,42,42
XS GIS Cut Line= 3
2200428.88751669734805.5667857882200018.67415232734760.433286041
 2199975.5465859734780.492619262
#Sta/Elev= 30
       0 1444.35     4.7  1443.4    16.8 1442.05    44.5  1435.9    57.1 1432.69
    89.2    1423   113.4 1419.29   121.4 1418.32   133.5 1417.69   169.7 1413.27
   211.3 1409.29   225.8  1407.3   238.1 1406.99   269.3 1404.58   286.4    1404
   296.31402.245   302.5 1401.68   309.1 1402.24   318.6 1404.33     335  1405.1
   370.9 1404.62   391.1 1405.71   407.2 1405.13   411.2 1405.96   415.4 1408.01
   424.2 1414.04   437.5 1424.69   441.9 1427.39   450.7 1429.87   460.3 1430.92
#Mann= 5 ,-1,0
       0      .1       0      30     .06       0     100     .07       0
   296.3    .045       0   309.1     .05       0
Bank Sta=296.3,309.1
XS Rating Curve= 0 ,0
Exp/Cntr(USF)=0,0
Exp/Cntr=0.3,0.1

Type RM Length L Ch R = 1 ,4013    ,19,19,19
XS GIS Cut Line= 3
2200416.85191676734763.9436693552200074.88040401734726.934199563
2199971.63501592734760.804383706
#Sta/Elev= 30
       0 1447.19    24.8 1441.71      54 1434.17    61.2 1431.59    65.1 1429.08
    69.1 1425.32    73.1 1423.02    86.6 1421.88    97.2 1423.48   101.3 1423.23
   121.4 1419.69   153.6 1415.47   177.7 1413.34   205.9 1408.84   278.3 1404.43
   290.8 1402.03   294.4 1401.33   302.4 1402.02   306.5 1403.31   334.6 1405.05
   355.2 1404.31   376.8 1404.56   388.9 1403.66   397.3 1404.04   401.8 1404.85
     410  1406.7   418.4 1410.94   439.4 1426.56   443.6 1428.26   452.6 1430.25
#Mann= 5 ,-1,0
       0     .06       0      90     .07       0     290     .05       0
   290.8    .045       0   302.4     .05       0
Bank Sta=290.8,302.4
XS Rating Curve= 0 ,0
Exp/Cntr(USF)=0,0
Exp/Cntr=0.3,0.1

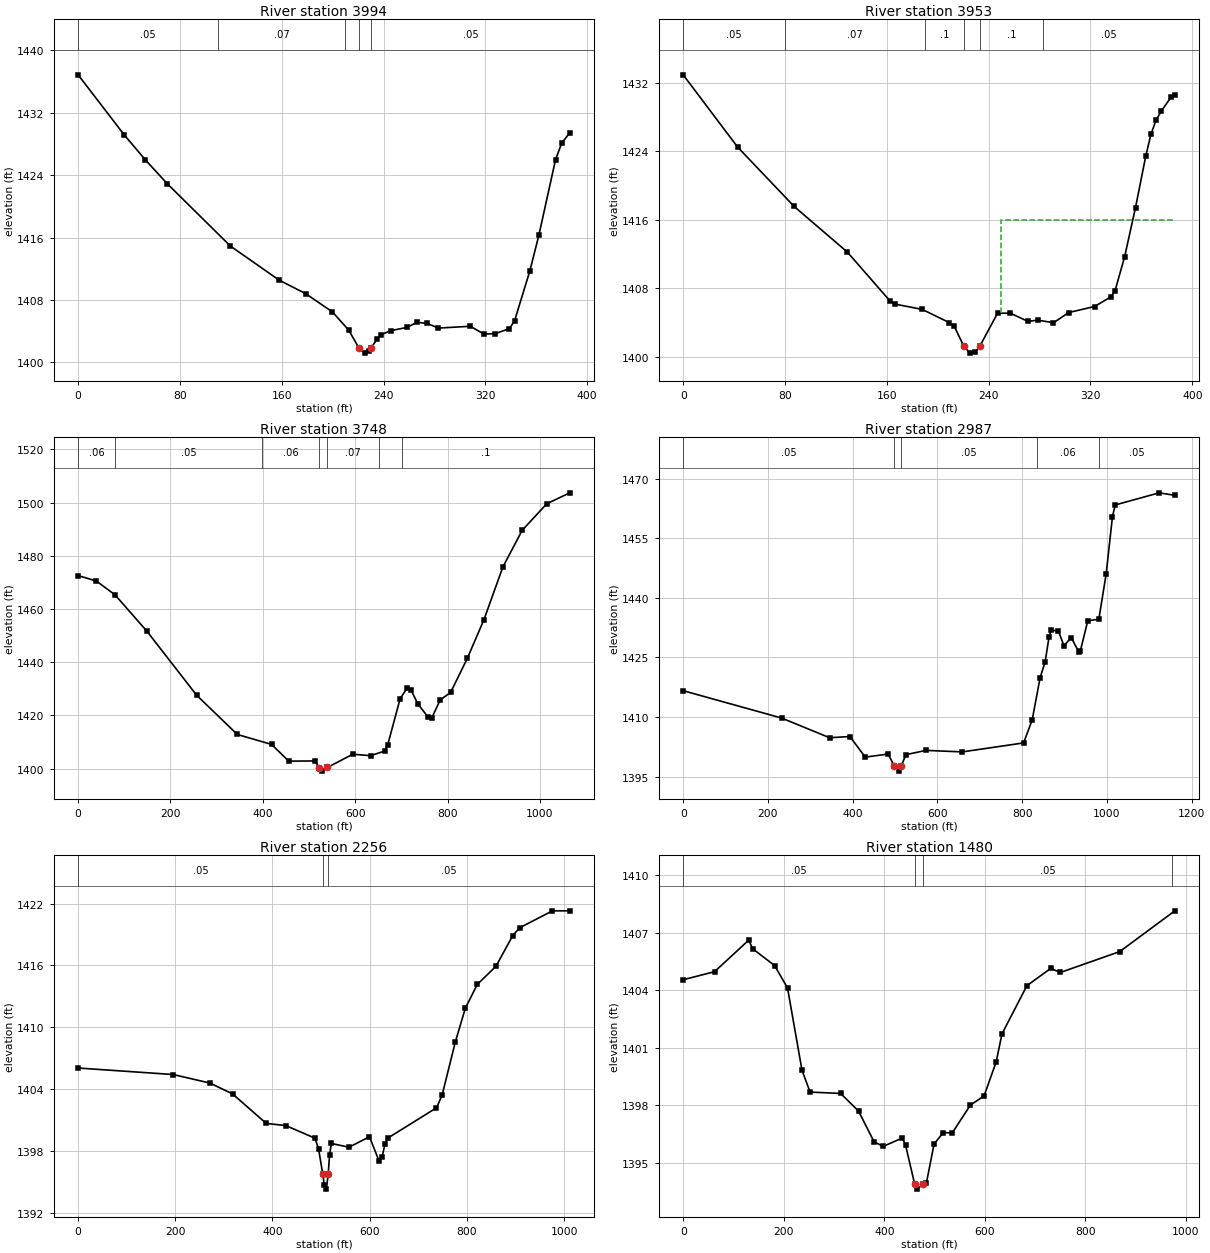
Type RM Length L Ch R = 1 ,3994    ,41.7,41.7,41.7
XS GIS Cut Line= 3
2200334.83933288734645.4130693532200093.55564324734720.966547929
2199961.13395498734737.214607838
#Sta/Elev= 30
       0 1436.85    36.3 1429.14    52.8 1425.96    69.9 1422.92   119.7  1414.9
   157.9 1410.55   178.8 1408.81   199.8 1406.47   212.6 1404.14   220.8  1401.8
   225.4 1401.19   228.6 1401.44   230.11401.797     235 1403.04   238.1 1403.56
   245.9 1404.08   258.3 1404.48   266.3 1405.14   274.4 1404.99     283  1404.4
   308.1 1404.63   318.9 1403.63   327.7 1403.69   338.9 1404.33   342.9 1405.33
     355 1411.76     362 1416.29   375.1 1425.97   379.9 1428.08   386.3 1429.43
#Mann= 5 ,-1,0
       0     .05       0     110     .07       0     210     .05       0
   220.8    .045       0   230.1     .05       0
Bank Sta=220.8,230.1
XS Rating Curve= 0 ,0
Exp/Cntr(USF)=0,0
Exp/Cntr=0.3,0.1

Type RM Length L Ch R = 1 ,3953    ,204.4,204.4,204.4
XS GIS Cut Line= 3
2200307.27566269734614.7091205732200065.99197304734690.262599149
2199933.57028478734706.510659058
#Sta/Elev= 30
       0 1432.91    42.7 1424.49    87.1 1417.56     129 1412.22   162.5 1406.52
   166.7 1406.14   187.7 1405.54   209.1 1403.99   212.8 1403.62   220.41401.268
   225.4 1400.43   229.6 1400.59   233.21401.276     247 1405.09   257.1 1405.09
   270.8 1404.14   278.8 1404.28   290.9 1403.97     303 1405.17   323.2 1405.87
   336.1    1407   339.3 1407.71   346.8 1411.65   355.4 1417.42   363.5 1423.46
   367.5 1425.96   371.5 1427.61   375.5 1428.65   383.6 1430.36   386.3 1430.54
#Mann= 6 ,-1,0
       0     .05       0      80     .07       0     190      .1       0
   220.4    .045       0   233.2      .1       0  282.84     .05       0
#XS Ineff= 2 , 0
                          249.89            1416
Permanent Ineff=
       F       F
Bank Sta=220.4,233.2
XS Rating Curve= 0 ,0
Exp/Cntr(USF)=0,0
Exp/Cntr=0.3,0.1

Type RM Length L Ch R = 1 ,3748    ,761.3,761.3,761.3
XS GIS Cut Line= 6
2200507.00998601734314.6170618392200301.12325868734352.843363345
2200206.29995751734383.2025545842199924.23916993734591.967885092
2199665.45261401734728.5844097582199561.38523684734766.333021924
#Sta/Elev= 30
       0 1472.56    39.4 1470.53    79.9 1465.32   149.2 1451.59   256.6 1427.59
   344.8 1412.81   418.9 1409.08   456.2 1402.78     513 1402.86   521.61400.387
   527.2 1399.03   539.8  1400.4   594.8 1405.39   633.4 1404.84     664 1406.59
   670.6 1408.99   697.5 1426.33   712.5 1430.25   720.7 1429.59   736.1 1424.24
   757.1 1419.52   766.1 1419.09   784.1 1425.79   806.7 1428.62   842.8  1441.4
   878.9 1455.97   919.9  1475.8   961.8  1489.6    1015 1499.57  1064.8 1503.68
#Mann= 7 ,-1,0
       0     .06       0      80     .05       0  398.81     .06       0
   521.6    .045       0   539.8     .07       0  650.79     .05       0
  701.44      .1       0
Bank Sta=521.6,539.8
XS Rating Curve= 0 ,0
Exp/Cntr(USF)=0,0
Exp/Cntr=0.3,0.1

Type RM Length L Ch R = 1 ,2987    ,731.1,731.1,731.1
XS GIS Cut Line= 6
2200359.39413951733764.7172430012200144.40277159733961.397952005
2200020.30754735734071.2208950822199906.54760426734113.874353096
2199793.83293468734163.6216289252199370.77374142734340.208218008
#Sta/Elev= 30
       0 1416.62   232.2 1409.74   345.5 1404.79   393.4 1405.08   429.6 1399.91
   483.6 1400.67   497.91397.732   508.4 1396.38   514.51397.654   525.6 1400.52
   572.6  1401.6   658.7 1401.22   803.3 1403.48   823.6 1409.28   842.2 1419.86
   854.2 1423.92   863.4  1430.2   868.2 1431.88   885.5 1431.64   898.5 1427.93
   915.8    1430   933.8  1426.3   937.4  1426.7   954.8 1434.25   980.8 1434.59
   998.1 1445.98  1012.9 1460.35  1019.5 1463.37  1123.3 1466.42  1160.2 1465.79
#Mann= 5 ,-1,0
       0     .05       0   497.9    .045       0   514.5     .05       0
  834.47     .06       0  981.01     .05       0
Bank Sta=497.9,514.5
XS Rating Curve= 0 ,0
Exp/Cntr(USF)=0,0
Exp/Cntr=0.3,0.1

Type RM Length L Ch R = 1 ,2256    ,775.3,775.3,775.3
XS GIS Cut Line= 6
2199940.02063443733410.0857344272199778.10658817733524.119955167
2199697.65432125733575.1342888332199552.97121167733655.377238587
2199348.75081959733821.2236916722199110.54952434733986.343440175
#Sta/Elev= 30
       0 1406.06   195.5 1405.43   271.4  1404.6   317.8 1403.55   387.2 1400.69
   427.5 1400.48   487.3 1399.26   494.8 1398.23   503.3 1395.81   506.6 1394.75
   510.9 1394.32   514.7 1395.81   517.5 1397.65   521.2 1398.75   557.4 1398.38
   599.6  1399.4   619.7    1397   625.4 1397.41   631.6 1398.71   636.7 1399.25
   737.5  1402.2   749.1 1403.44   776.3 1408.59   796.8 1411.85   821.4 1414.16
     860 1415.93   894.4  1418.9   908.8 1419.66   976.2  1421.3  1011.8  1421.3
#Mann= 3 ,-1,0
       0     .05       0   503.3    .045       0   514.7     .05       0
Bank Sta=503.3,514.7
XS Rating Curve= 0 ,0
Exp/Cntr(USF)=0,0
Exp/Cntr=0.3,0.1

Type RM Length L Ch R = 1 ,1480    ,41.9,41.9,41.9
XS GIS Cut Line= 5
2199420.98072961732771.9133979272199117.34112122733013.795682673
2199042.44090016 733110.01220901  2198986.800304733138.768960072
  2198652.171176733366.904390335
#Sta/Elev= 30
       0 1404.55    62.4 1404.97   130.4 1406.62   138.1 1406.17   181.8 1405.29
   207.5 1404.12   236.3 1399.82   252.4 1398.68     313 1398.61   348.7 1397.69
   379.5 1396.09   397.6 1395.84   435.7 1396.28   442.2 1395.91   460.31393.881
   465.6 1393.61     477 1393.88   483.7 1393.93   498.9 1395.96     517 1396.56
   535.2 1396.55   571.2    1398   598.4 1398.48   622.5 1400.26     634 1401.72
   683.6 1404.24   730.9 1405.14   750.2 1404.93   868.2 1406.02   977.8 1408.15
#Mann= 4 ,-1,0
       0     .05       0   460.3    .045       0     477     .05       0
  972.77     .06       0
Bank Sta=460.3,477
XS Rating Curve= 0 ,0
Exp/Cntr(USF)=0,0
Exp/Cntr=0.3,0.1

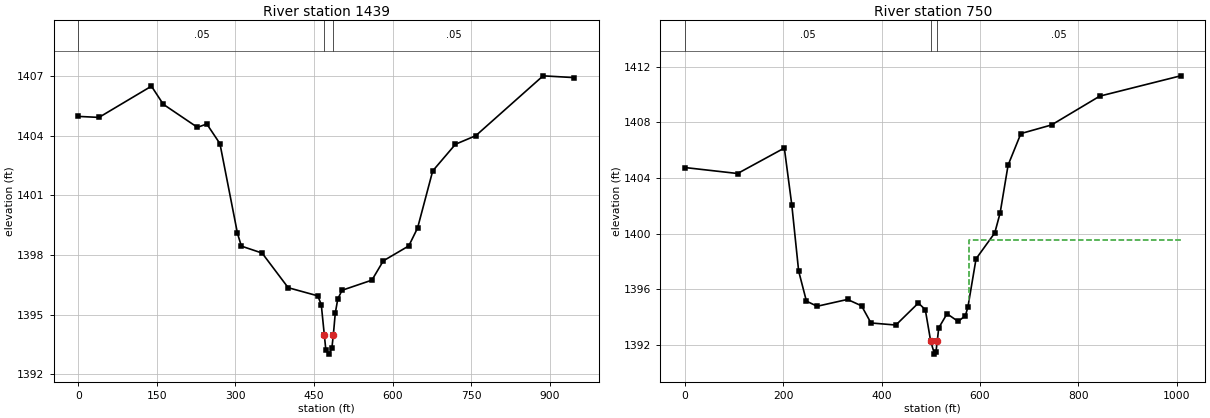
Type RM Length L Ch R = 1 ,1439    ,688.5,688.5,688.5
XS GIS Cut Line= 5
2199385.54543563732709.4658891852199091.06804553 732973.29135764
 2199024.2906448733076.1942374522198968.46035894733095.899044225
2198658.65700802  733297.3259579
#Sta/Elev= 30
       0 1404.96    39.4 1404.91   139.6 1406.48   162.2 1405.57   227.4 1404.41
   245.3 1404.58   270.4 1403.59   303.9 1399.08   311.3 1398.44   350.9 1398.09
   400.7 1396.35   457.2 1395.94   463.9  1395.5   469.7 1393.98   472.6 1393.23
   478.4 1393.01   484.1  1393.3     487 1393.99   490.6 1395.06   495.4 1395.78
   503.6 1396.22   560.6 1396.73   582.4  1397.7     631 1398.45   647.8 1399.35
   676.7 1402.22   720.1 1403.56   758.9 1403.99   887.5    1407   946.8 1406.91
#Mann= 3 ,-1,0
       0     .05       0   469.7    .045       0     487     .05       0
Bank Sta=469.7,487
XS Rating Curve= 0 ,0
Exp/Cntr(USF)=0,0
Exp/Cntr=0.3,0.1

Type RM Length L Ch R = 1 ,750     ,663.5,663.5,663.5
XS GIS Cut Line= 6
 2199102.5226375732195.8466930842198782.86087526732401.242607757
2198720.67661643732444.2881253362198527.26361743 732621.76414834
2198456.80870584732683.6455862522198302.55343692  732804.3668015
#Sta/Elev= 30
       0 1404.75   107.3 1404.32   202.3 1406.15   217.5 1402.06   231.4 1397.31
   247.2 1395.15     269 1394.78   330.7 1395.27   359.3 1394.81   378.4 1393.58
     429 1393.43   474.7 1395.01   488.8 1394.54   499.71392.289   507.5 1391.34
   510.4 1391.47   513.2 1392.29   516.1 1393.22     533 1394.24   555.6 1393.69
   570.3  1394.1   575.5 1394.73     592 1398.19     630 1400.05   640.9 1401.48
   657.1 1404.92   683.1 1407.19   745.4 1407.81   843.4 1409.88  1007.8 1411.34
#Mann= 3 ,-1,0
       0     .05       0   499.7    .045       0   513.2     .05       0
#XS Ineff= 1 ,-1
  577.531007.755 1399.56
Permanent Ineff=
       F
Bank Sta=499.7,513.2
XS Rating Curve= 0 ,0
Exp/Cntr(USF)=0,0
Exp/Cntr=0.3,0.1