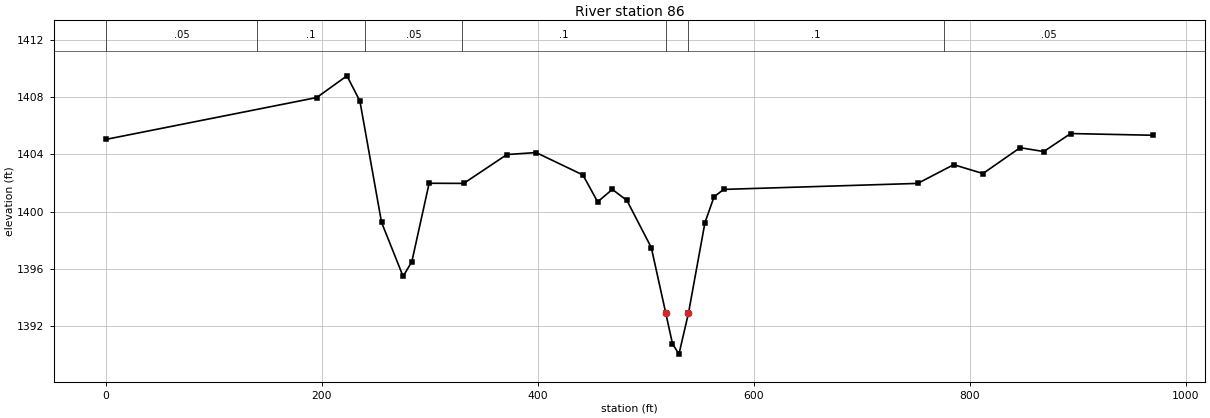
HEC-RAS study BRUSHRN2.prj: BRUSHRN2

--- BRUSHRN2.g01 (geometry) --- (continued)

Type RM Length L Ch R = 1 ,86      ,,,
XS GIS Cut Line= 3
2198791.12117836732037.3989039142198405.89392857732055.284454797
2197888.58876458732326.319341252
#Sta/Elev= 30
       0 1405.05   195.2 1407.98   223.2  1409.5   235.2 1407.73   255.2 1399.25
   275.2 1395.46   283.3  1396.5   299.3 1401.98   331.3 1401.97   371.3 1403.99
   398.3 1404.13   441.7 1402.56   455.3 1400.68   468.9 1401.55   482.4 1400.78
     505 1397.48   518.31392.924   524.6 1390.75   530.6 1390.02   539.4 1392.88
   554.7 1399.23   563.1 1401.03     572 1401.55   751.7 1401.97     785 1403.28
   812.1 1402.66   846.5 1404.47   868.4  1404.2   893.3 1405.46   969.6 1405.34
#Mann= 7 ,-1,0
       0     .05       0     140      .1       0     240     .05       0
     330      .1       0   518.3    .045       0   539.4      .1       0
  775.64     .05       0
Bank Sta=518.3,539.4
XS Rating Curve= 0 ,0
Exp/Cntr(USF)=0,0
Exp/Cntr=0.3,0.1
LCMann Table=0

Chan Stop Cuts=-1
Use User Specified Reach Order=0
Composite Channel Slope=5