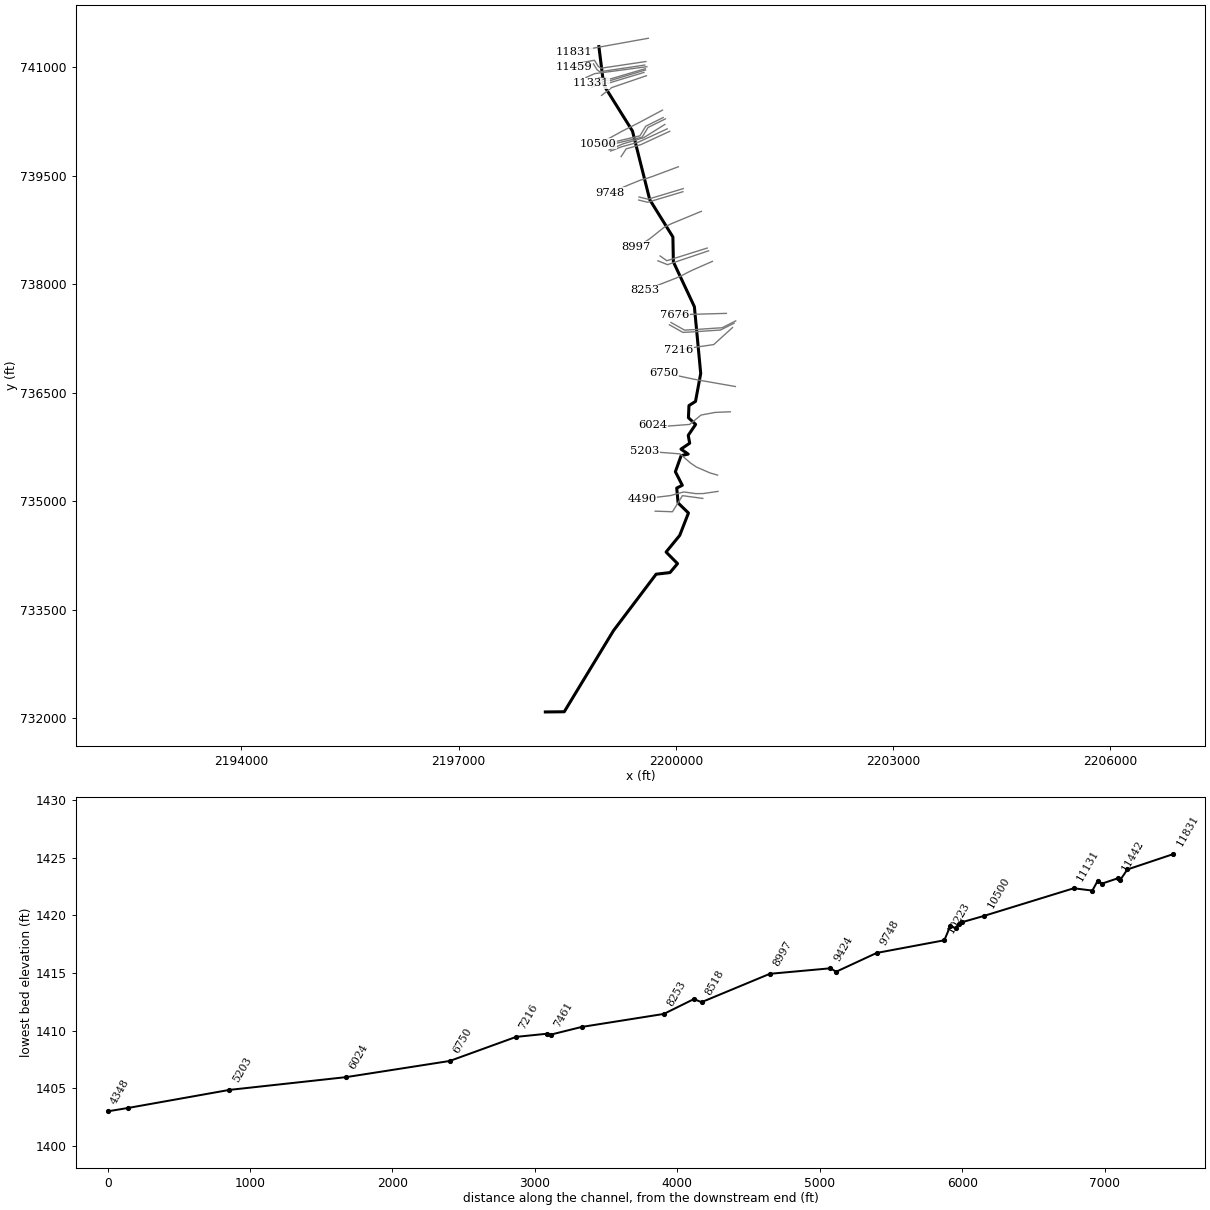
--- BRUSHRN2.prj (project) ---

Proj Title=BRUSHRN2
Current Plan=p01
Default Exp/Contr=0,0
English Units
Geom File=g01
Flow File=f01
Plan File=p01
BEGIN DESCRIPTION:
Stream Name: Brush Run (II)
Flood Zone:  AFH
Upshur County, WV
HEC-RAS Version: RAS 6.3
Vertical Datum: NAVD88
Projection: NAD 1983 StatePlane West Virginia S FIPS 4702 (US Feet)
Terrain: 1-meter LIDAR (FEMA Region III 3DEP collected 2016-2018)
Land Use: 2019 NLCD
Hydrologic Method:
WV SIR2010-5033 regression equations
Additional Model Notes:
None
END DESCRIPTION:
DSS Export Rating Curves= 0
DSS Export Rating Curve Sorted= 0
DSS Export Volume Flow Curves= 0
DXF OffsetX= 0
DXF OffsetY= 0
DXF ScaleX= 0
DXF ScaleY= 0

--- BRUSHRN2.p01 (plan) ---

Plan Title=Floodplain
Program Version=4.00
Geom File=g01
Flow File=f01
K Sum by GR=0
Std Step Tol=0.01
Critical Tol=0.01
Num of Std Step Trials=20
Max Error Tol=0.3
Flow Tol Ratio=0.001
Split Flow NTrial=30
Split Flow Tol=0.02
Split Flow Ratio=0.02
Log Output Level=0
Friction Slope Method=1
Unsteady Friction Slope Method=2
Unsteady Bridges Friction Slope Method=1
Global Log Level=0
CheckData=False
Run HTab=0
Run UNet=0
Run PostProcess=0
UNET Theta=0
UNET Theta Warmup=0
UNET ZTol=0
UNET ZSATol=0
UNET MxIter=0
UNET MaxInSteps=0
UNET DtIC=0
UNET DtMin=0
UNET MaxCRTS=0
UNET WFStab=0
UNET SFStab=0
UNET WFX=0
UNET SFX=0
UNET DSS MLevel=0
UNET DZMax Abort=0
UNET Convert EG Bridges=0
UNET Use Existing IB Tables=0
UNET Froude Limit=0
UNET Froude Power=0
Write IC File=0
Echo Input=False
Echo Output=False
Write Detailed=0

--- BRUSHRN2.f01 (steady flow) ---

Flow Title=Flows
Program Version=6.31
Number of Profiles= 1
Profile Names=01pct
River Rch & RM=BRUSHRN2,Main            ,11831
     378
River Rch & RM=BRUSHRN2,Main            ,8518
     432
River Rch & RM=BRUSHRN2,Main            ,5203
     482
River Rch & RM=BRUSHRN2,Main            ,4490
     539
Boundary for River Rch & Prof#=BRUSHRN2,Main            , 1
Up Type= 0
Dn Type= 3
Dn Slope=0.00184
DSS Import GetInterval= 0
DSS Import GetPeak= 0
DSS Import FillOption= 0

--- BRUSHRN2.g01 (geometry) ---

Geom Title=Geometry
Program Version=6.31

River Reach=BRUSHRN2        ,Main
Reach XY= 30
2198937.42548073741281.350630068     2199004.029      740751.106
      2199401.31      740114.792     2199639.856      739166.816
     2199959.673      738651.578     2199966.054      738308.153
     2200256.282      737688.751     2200343.791      736766.531
     2200271.935      736380.124      2200181.65      736322.319
     2200174.124      736154.884     2200273.623      736061.996
     2200171.434      735911.273     2200191.494      735802.817
     2200071.334      735720.974     2200170.919      735652.152
     2200073.509      735630.861     2199993.755       735408.54
     2200089.591      735221.132     2200012.585      735183.158
     2200031.386      734977.463     2200174.382      734838.903
     2200054.078      734529.788     2199865.496      734299.112
     2200023.802       734139.26     2199919.267      734015.466
     2199727.966      733993.403     2199138.783      733213.091
     2198458.801      732092.817     2198197.762      732090.098

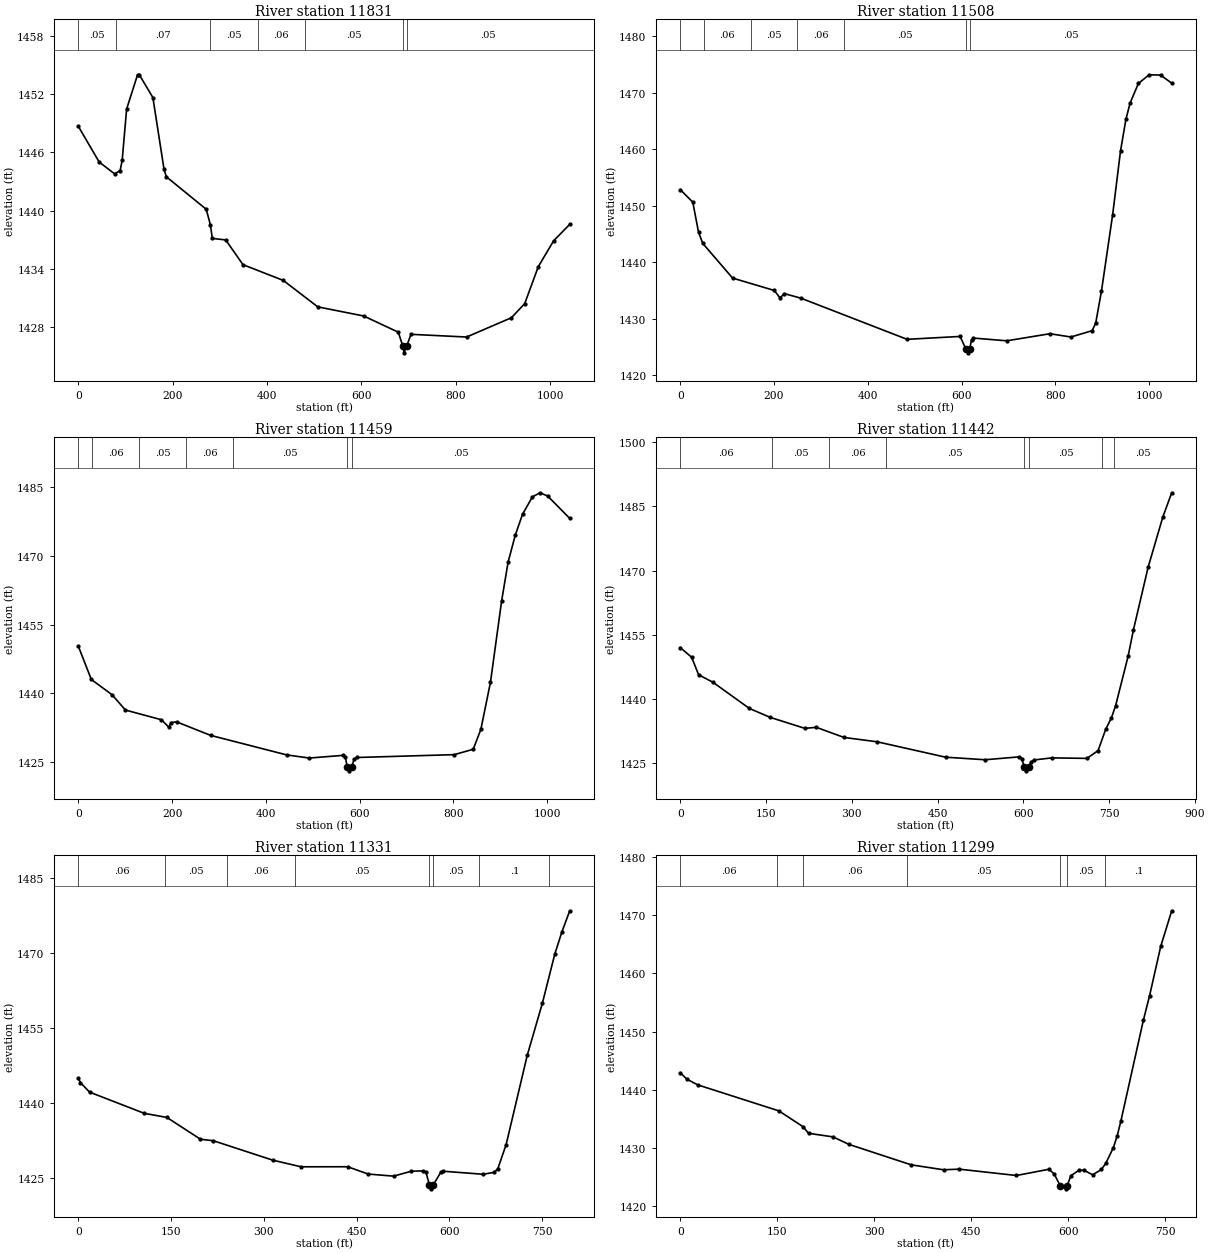
Type RM Length L Ch R = 1 ,11831   ,323.6,323.6,323.6
XS GIS Cut Line= 2
 2199619.7529936741396.5291962032198594.49818454 741212.03285979
#Sta/Elev= 30
       0 1448.69    44.3    1445    76.8 1443.79    88.6 1444.11      93 1445.17
   102.4 1450.46   125.6    1454   129.6 1453.98   158.1 1451.65   181.6 1444.29
   186.5 1443.49   271.2 1440.13     280 1438.53   284.1 1437.13   312.5 1436.97
   349.1 1434.42   434.4  1432.8   507.6 1430.07   604.9 1429.13   678.3 1427.46
     688    1426   690.5 1425.33  695.95    1426   705.2 1427.24     823 1426.96
   918.1 1428.95   946.3 1430.41     975 1434.21  1007.5 1436.881041.723 1438.58
#Mann= 7 ,-1,0
       0     .05       0      80     .07       0     280     .05       0
     380     .06       0     480     .05       0     688    .045       0
  695.95     .05       0
Bank Sta=688,695.95
XS Rating Curve= 0 ,0
Exp/Cntr(USF)=0,0
Exp/Cntr=0.3,0.1

Type RM Length L Ch R = 1 ,11508   ,47.6,48.3,47.9
XS GIS Cut Line= 5
2199586.59287653 741075.058584942198964.75354668740982.562770644
2198927.97810244741009.3085482722198875.60095459741092.889103359
2198604.79995611741042.740770307
#Sta/Elev= 30
       0 1452.85    26.7 1450.64      39 1445.31    48.1 1443.33   111.6 1437.21
   200.6 1435.02   212.7 1433.71     222 1434.46   257.2 1433.66   483.7 1426.38
   596.9 1426.89   609.3 1424.64   613.1 1423.99  617.17 1424.64   621.2 1426.27
   625.2  1426.6   696.4 1426.12   788.5 1427.37   833.2 1426.79   878.5 1427.91
   886.1 1429.26   898.3 1434.86   922.2  1448.4     939 1459.68   950.5 1465.27
   959.3 1468.13   977.1 1471.62    1000 1473.16  1024.4 1473.111048.195 1471.68
#Mann= 7 ,-1,0
       0     .05       0      50     .06       0     150     .05       0
     250     .06       0     350     .05       0   609.3    .045       0
  617.17     .05       0
Bank Sta=609.3,617.17
XS Rating Curve= 0 ,0
Exp/Cntr(USF)=0,0
Exp/Cntr=0.3,0.1

Type RM Length L Ch R = 1 ,11459   ,17.8,17.5,17.3
XS GIS Cut Line= 5
2199571.54837661 741026.581862992198949.70904677740934.086048694
2198912.93360253740960.8318263222198860.55645468741044.412381408
2198589.75545619740994.264048356
#Sta/Elev= 30
       0 1450.31    27.7 1443.04    72.2 1439.69   100.5 1436.37   177.3 1434.25
   193.5 1432.59   197.5 1433.63   209.7 1433.79   282.3 1430.84   444.2 1426.59
   492.7  1425.9   565.5 1426.49   569.6 1426.08   573.6 1423.99   577.7 1423.11
  582.82 1423.99   588.6  1425.7   593.8 1426.02   801.7 1426.64   842.3 1427.81
   858.6 1432.14   879.1 1442.43   902.9 1460.16   916.6 1468.56   931.8 1474.44
   947.5 1479.06   968.4 1482.84   984.7 1483.75    1001 1483.051048.195 1478.16
#Mann= 7 ,-1,0
       0     .05       0      30     .06       0     130     .05       0
     230     .06       0     330     .05       0   573.6    .045       0
  582.82     .05       0
Bank Sta=573.6,582.82
XS Rating Curve= 0 ,0
Exp/Cntr(USF)=0,0
Exp/Cntr=0.3,0.1

Type RM Length L Ch R = 1 ,11442   ,110.9,111.2,108.5
XS GIS Cut Line= 3
2199599.96576534741003.7365112662198878.94417679740907.897474767
2198758.58817747740854.405919511
#Sta/Elev= 30
       0 1452.03    19.9 1449.76    32.1 1445.67    57.3 1443.91   120.8 1437.81
   157.2 1435.72   217.7 1433.16   237.9 1433.39   286.3 1431.03     344 1430.02
   463.8 1426.42   532.8 1425.82     593  1426.5     597 1426.09  601.54 1424.05
   605.1 1423.23   609.1 1424.05   613.1 1425.26   618.3 1425.77   649.5 1426.26
   710.9 1426.14   730.4 1427.96   743.6 1432.89   753.8 1435.63     761 1438.43
   782.9 1450.01   792.1 1456.11   817.9 1470.81   843.6 1482.54   859.1 1488.19
#Mann= 8 ,-1,0
       0     .06       0     160     .05       0     260     .06       0
     360     .05       0  601.54    .045       0   609.1     .05       0
  737.36      .1       0  757.36     .05       0
Bank Sta=601.54,609.1
XS Rating Curve= 0 ,0
Exp/Cntr(USF)=0,0
Exp/Cntr=0.3,0.1

Type RM Length L Ch R = 1 ,11331   ,27.6,31.3,32.2
XS GIS Cut Line= 4
2199577.67761732740975.8763262372199099.59684222740835.460993692
2198936.89336165740847.7194751042198827.68143634740771.939771826
#Sta/Elev= 30
       0 1444.91     3.4 1444.04    18.2 1442.12   106.5 1437.88   143.3 1437.05
   197.5 1432.69   218.4 1432.39   314.2 1428.51   360.1 1427.18   435.4 1427.19
   468.5 1425.73   509.7 1425.31   537.8 1426.28   557.9 1426.37   561.9 1426.09
   567.5 1423.59   569.9 1422.77   573.9 1423.58   573.9 1423.59   585.9 1426.08
     590 1426.29   654.1 1425.69   672.4 1426.07   678.2 1426.83   691.5  1431.6
   725.6 1449.45   750.1  1459.9   770.1 1469.69   781.4 1474.08794.3672  1478.4
#Mann= 8 ,-1,0
       0     .06       0     140     .05       0     240     .06       0
     350     .05       0   567.5    .045       0   573.9     .05       0
  648.27      .1       0  761.44     .05       0
Bank Sta=567.5,573.9
XS Rating Curve= 0 ,0
Exp/Cntr(USF)=0,0
Exp/Cntr=0.3,0.1

Type RM Length L Ch R = 1 ,11299   ,39,37.3,37.6
XS GIS Cut Line= 4
2199582.13524692 740959.160215222199091.79599041740810.944030866
 2198977.0120281740818.7448826742198862.22806578740751.880438605
#Sta/Elev= 30
       0 1442.94    10.4 1441.82    27.1 1440.85   152.5 1436.39   190.1 1433.66
   198.4 1432.54   236.1 1431.93   261.1 1430.63   357.2 1427.13   407.2 1426.28
   431.2 1426.39   519.9  1425.3   570.3 1426.37   578.3 1425.57     588 1423.49
   596.1 1423.01  598.27 1423.49   604.1 1425.25   616.1 1426.16   624.1 1426.22
   637.8 1425.42   651.4 1426.33   658.3 1427.42   669.9 1430.08   675.9 1432.13
   681.7 1434.73   716.2  1451.9   725.8  1456.1   743.1  1464.6760.1383 1470.73
#Mann= 7 ,-1,0
       0     .06       0     150     .05       0     190     .06       0
     350     .05       0     588    .045       0  598.27     .05       0
   657.3      .1       0
Bank Sta=588,598.27
XS Rating Curve= 0 ,0
Exp/Cntr(USF)=0,0
Exp/Cntr=0.3,0.1

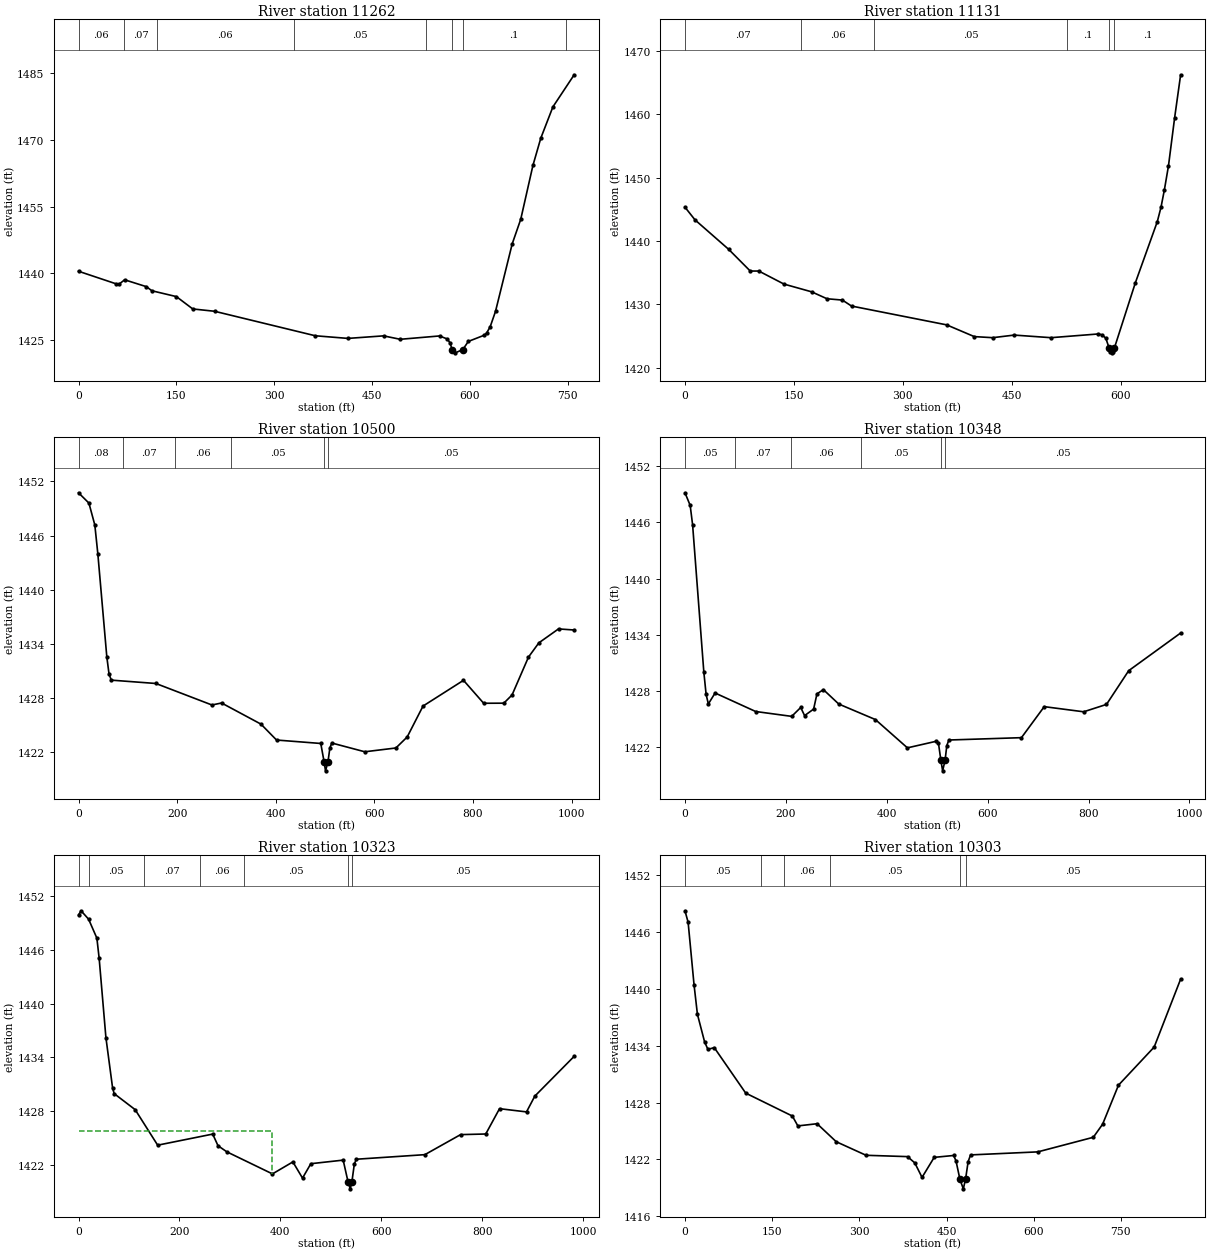
Type RM Length L Ch R = 1 ,11262   ,122.2,131.1,139.1
XS GIS Cut Line= 4
 2199559.8470989740924.6135857842199069.50784239740776.397401431
2198954.72388007740784.1982532392198839.93991775740717.333809169
#Sta/Elev= 30
       0 1440.47    58.2 1437.62    62.3 1437.58    70.7 1438.55   104.1 1437.01
   112.5 1436.09   150.1 1434.78   175.2 1432.01   208.6 1431.49   363.2 1425.99
   413.2  1425.4   467.8 1425.97   493.4  1425.2   553.7 1425.95   565.7 1425.26
   569.7 1424.41  573.05 1422.88   577.7 1422.16   589.3 1422.88   597.8 1424.72
   621.8 1426.09   625.8 1426.58   631.4 1428.04   639.5 1431.46   665.1 1446.61
   678.2 1452.13   696.9 1464.22   708.9 1470.31   727.5 1477.35760.1383 1484.56
#Mann= 8 ,-1,0
       0     .06       0      70     .07       0     120     .06       0
     330     .05       0  532.25      .1       0  573.05    .045       0
   589.3      .1       0   747.3     .05       0
Bank Sta=573.05,589.3
XS Rating Curve= 0 ,0
Exp/Cntr(USF)=0,0
Exp/Cntr=0.3,0.1

Type RM Length L Ch R = 1 ,11131   ,631.2,630.9,629.2
XS GIS Cut Line= 3
2199593.27932093740878.9228823372199114.08413844740715.104994367
2198974.78321329740607.007476455
#Sta/Elev= 30
       0 1445.33    13.8 1443.33    60.3 1438.67    89.9 1435.26   101.7 1435.26
   136.4  1433.2   174.5 1431.98   195.6 1430.89   216.8 1430.68   229.4 1429.74
   360.5 1426.77   398.5 1424.92   423.9 1424.75   453.5 1425.16   504.2 1424.75
   569.6 1425.34   574.7 1425.19   579.7 1424.66  584.31  1423.1   586.1 1422.57
   587.9 1422.36   589.8 1422.53  591.43  1423.1   620.3 1433.38   650.6 1443.05
   655.7 1445.32   660.3 1448.02     666 1451.85   674.5 1459.45682.7462 1466.21
#Mann= 6 ,-1,0
       0     .07       0     160     .06       0     260     .05       0
  526.42      .1       0  584.31    .045       0  591.43      .1       0
Bank Sta=584.31,591.43
XS Rating Curve= 0 ,0
Exp/Cntr(USF)=0,0
Exp/Cntr=0.3,0.1

Type RM Length L Ch R = 1 ,10500   ,154,152.5,150
XS GIS Cut Line= 6
2199814.73053068740403.3906454292199482.30173358740226.069805846
2199259.01313818740113.584794596 2199099.8021705740025.549865678
2199013.19341984739980.914784342  2198923.387169739938.743936926
#Sta/Elev= 30
       0 1450.74    21.1  1449.6    33.1 1447.17    39.2 1443.98    57.4 1432.58
    61.9 1430.68    66.5    1430   156.9 1429.63   270.6 1427.25   290.2 1427.47
   370.1 1425.13   401.7 1423.37   491.4 1422.99  498.29 1420.92     501 1419.96
  505.89 1420.92   509.9  1422.5   513.7 1423.04   580.7 1422.07   643.8 1422.49
   666.7 1423.71   698.8 1427.13   780.9 1429.98   821.8 1427.44   862.7 1427.45
   879.4 1428.36   912.7 1432.55   933.8 1434.13   973.6 1435.671005.379 1435.55
#Mann= 6 ,-1,0
       0     .08       0      90     .07       0  195.42     .06       0
  309.22     .05       0  498.29    .045       0  505.89     .05       0
Bank Sta=498.29,505.89
XS Rating Curve= 0 ,0
Exp/Cntr(USF)=0,0
Exp/Cntr=0.3,0.1

Type RM Length L Ch R = 1 ,10348   ,24.8,24.8,24.7
XS GIS Cut Line= 4
2199825.69041529740301.4030251072199584.97841664740182.049992443
 2199503.7381171740048.6554265252198961.13315347739920.275693912
#Sta/Elev= 30
       0 1449.18    10.3 1447.83    15.1 1445.76    37.4 1429.97    41.9  1427.6
    46.3 1426.58    59.7 1427.75   140.1 1425.77   211.5 1425.25   229.4  1426.2
   237.1 1425.33     255 1426.03   261.6 1427.66   274.4 1428.11   304.8 1426.57
   377.4 1424.91   440.9 1421.88   498.4 1422.59   502.5 1422.35   507.2 1420.56
   510.7 1419.42  515.58 1420.56     519 1422.13   523.1 1422.72   666.9 1422.97
   712.1 1426.29   790.2 1425.74   835.5 1426.53   879.5 1430.14982.4487 1434.17
#Mann= 6 ,-1,0
       0     .05       0     100     .07       0     210     .06       0
  348.68     .05       0   507.2    .045       0  515.58     .05       0
Bank Sta=507.2,515.58
XS Rating Curve= 0 ,0
Exp/Cntr(USF)=0,0
Exp/Cntr=0.3,0.1

Type RM Length L Ch R = 1 ,10323   ,19.6,20.2,20.8
XS GIS Cut Line= 4
2199856.78238178740283.3496252092199616.07038313740163.996592545
2199534.83008359740030.6020266272198992.22511997739902.222294013
#Sta/Elev= 30
       0  1449.9     5.1 1450.37      20 1449.43    36.4 1447.31    40.9 1445.07
    54.3  1436.2    67.6 1430.55    70.7 1429.93   112.3 1428.14   156.9 1424.17
     266 1425.41   276.5 1424.11   293.9 1423.43   384.4 1420.96   424.9  1422.3
     444 1420.49   460.5  1422.1   524.6  1422.5   534.5 1420.01   538.6 1419.29
  541.73 1420.01   546.8  1422.1   550.9  1422.6   686.5 1423.11   757.3 1425.35
   807.2 1425.42   834.5 1428.25     888 1427.89   904.4 1429.65982.4487  1434.1
#Mann= 7 ,-1,0
       0     .08       0      20     .05       0     130     .07       0
     240     .06       0  328.68     .05       0   534.5    .045       0
  541.73     .05       0
#XS Ineff= 2 , 0
          384.36 1425.74
Permanent Ineff=
       F       F
Bank Sta=534.5,541.73
XS Rating Curve= 0 ,0
Exp/Cntr(USF)=0,0
Exp/Cntr=0.3,0.1

Type RM Length L Ch R = 1 ,10303   ,37.8,37.3,37.2
XS GIS Cut Line= 4
2199848.75864849740206.1211923082199555.89238347740022.578293338
2199269.04391841 739937.326127152199078.48025281739854.079894284
#Sta/Elev= 30
       0 1448.23     5.4 1447.02    15.6 1440.42    21.4 1437.31    33.7 1434.41
    39.4 1433.61    50.4 1433.79   104.5 1428.99   184.8 1426.57   194.2 1425.53
   227.3 1425.76   260.3 1423.86   311.6 1422.43   382.9 1422.29   395.4 1421.63
   407.9  1420.1   428.8 1422.21   462.2 1422.41   466.3 1421.85  473.02 1419.91
   478.9 1418.89  482.77 1419.91   487.2 1421.76   491.4 1422.47   607.1 1422.79
   702.6 1424.33   718.6 1425.71   745.9 1429.83   807.3 1433.85852.8299 1441.02
#Mann= 6 ,-1,0
       0     .05       0     130     .07       0     170     .06       0
     250     .05       0  473.02    .045       0  482.77     .05       0
Bank Sta=473.02,482.77
XS Rating Curve= 0 ,0
Exp/Cntr(USF)=0,0
Exp/Cntr=0.3,0.1

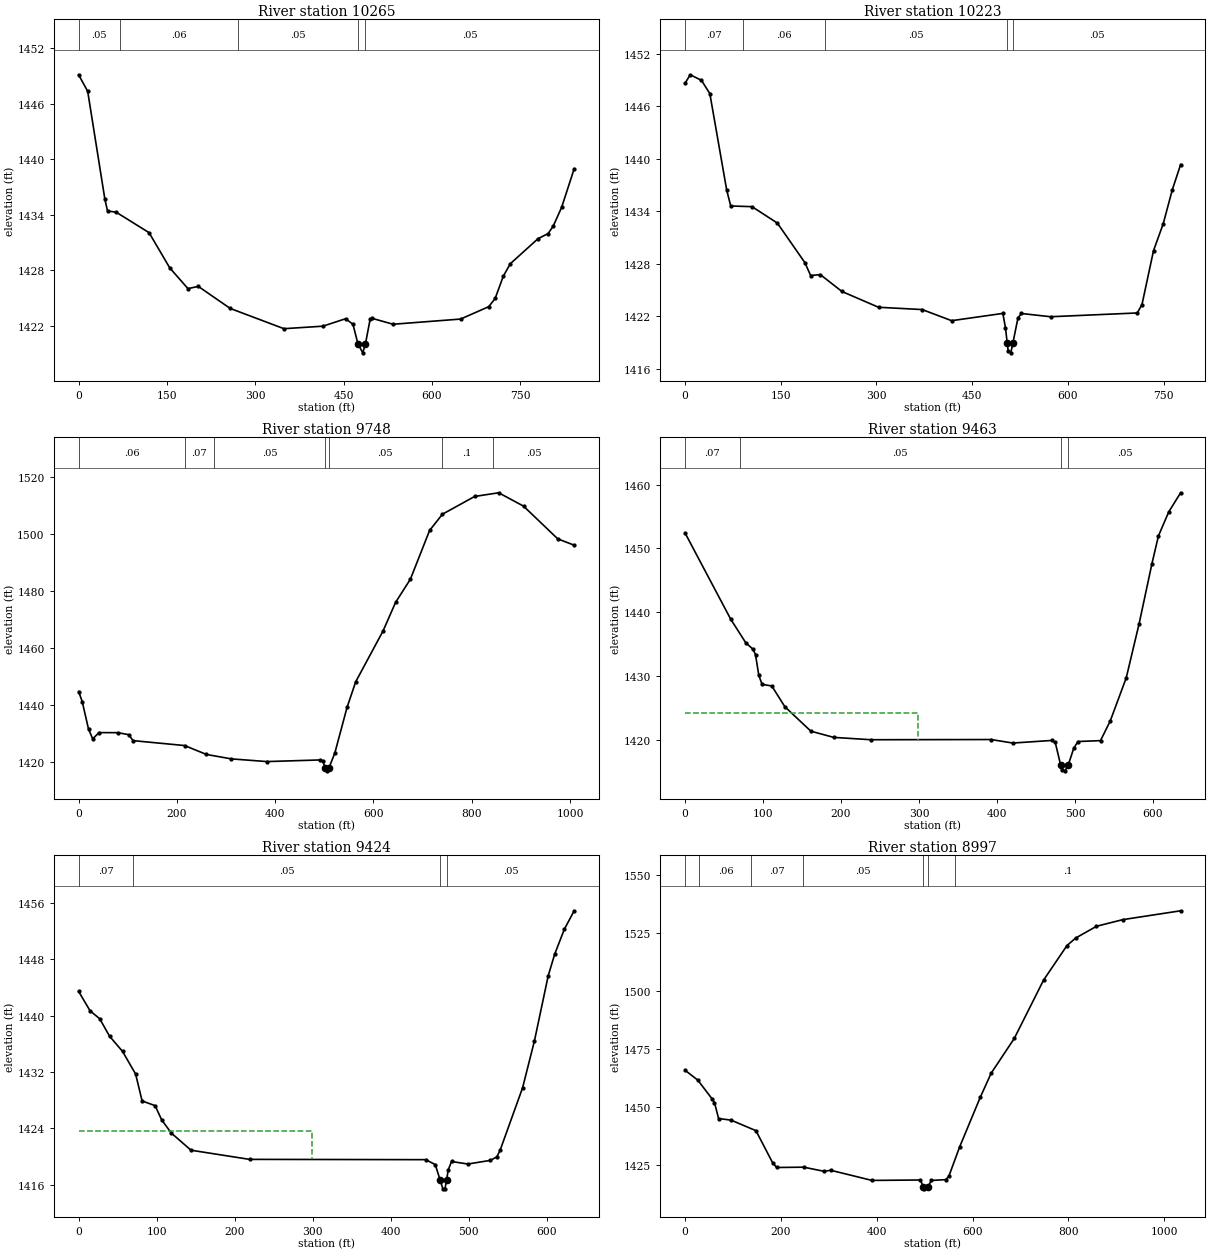
Type RM Length L Ch R = 1 ,10265   ,43.1,42.8,42.9
XS GIS Cut Line= 4
 2199880.7042001740145.1463312262199481.71883425739960.787575973
2199245.96974578739895.3901323042199098.94147844739838.876386725
#Sta/Elev= 30
       0 1449.15    15.4 1447.36    44.6 1435.69    49.1 1434.43    63.7  1434.3
   119.6 1432.09   154.8 1428.28   185.7 1426.04   203.3 1426.28   257.4  1423.9
   348.7 1421.71   414.8 1421.98   453.6 1422.79     466 1422.18   474.3  1420.1
   482.6  1419.1  487.24  1420.1   495.1 1422.71   498.9 1422.82   534.2 1422.19
   648.7 1422.75   696.6 1424.09   707.5 1424.98   721.3 1427.38   733.2 1428.73
   780.4 1431.44   797.5 1431.99   806.1  1432.8   820.4 1434.82   841.7 1438.99
#Mann= 5 ,-1,0
       0     .05       0      70     .06       0     270     .05       0
   474.3    .045       0  487.24     .05       0
Bank Sta=474.3,487.24
XS Rating Curve= 0 ,0
Exp/Cntr(USF)=0,0
Exp/Cntr=0.3,0.1

Type RM Length L Ch R = 1 ,10223   ,474.5,475.1,476.2
XS GIS Cut Line= 4
2199915.40656453740111.1709250112199516.42119868739926.812169759
2199313.69158876739868.2937841212199245.08458299739762.250820713
#Sta/Elev= 30
       0 1448.62       8 1449.58    25.6 1448.95    38.8 1447.43    65.2 1436.43
    71.5 1434.61   104.9 1434.53   144.6 1432.66   187.8 1428.14   196.8 1426.67
   211.9 1426.78   245.9 1424.85   303.2 1423.05   371.6 1422.79   417.8 1421.52
   498.1 1422.35   502.2 1420.71  504.91 1418.99   506.4  1418.1   510.6 1417.85
   513.9 1418.99   521.8 1421.84   527.2 1422.34     573 1421.97   708.8  1422.4
   716.2 1423.36   734.3 1429.51   749.5 1432.58   763.8 1436.47   776.8 1439.34
#Mann= 5 ,-1,0
       0     .07       0      90     .06       0     220     .05       0
  504.91    .045       0   513.9     .05       0
Bank Sta=504.91,513.9
XS Rating Curve= 0 ,0
Exp/Cntr(USF)=0,0
Exp/Cntr=0.3,0.1

Type RM Length L Ch R = 1 ,9748    ,284,284.5,284.2
XS GIS Cut Line= 6
  2200034.951875  739621.52639552199681.02607368739489.085059345
2199609.29623026739464.8328112512199511.65502134739437.169808835
2199359.94863184739375.6840394292199093.44522785739262.212481588
#Sta/Elev= 30
       0 1444.64     7.3 1441.13    20.1 1431.45    28.7    1428    41.5 1430.21
      80 1430.18   101.6 1429.49   110.9 1427.38   215.7 1425.65     260 1422.52
   310.7 1420.96     383 1420.01   492.2 1420.59   496.4 1420.31  502.25 1417.71
   504.7 1416.75   509.3 1417.71   521.3 1422.99   546.2 1439.05   563.9 1448.11
   619.5 1465.97   644.9    1476   675.2 1484.22   714.2 1501.34   740.3 1507.06
     806 1513.32   854.8 1514.61   905.4 1509.91     975  1498.41008.458 1496.16
#Mann= 7 ,-1,0
       0     .06       0  215.72     .07       0  275.72     .05       0
  502.25    .045       0   509.3     .05       0   738.8      .1       0
  842.84     .05       0
Bank Sta=502.25,509.3
XS Rating Curve= 0 ,0
Exp/Cntr(USF)=0,0
Exp/Cntr=0.3,0.1

Type RM Length L Ch R = 1 ,9463    ,39.4,39.5,39.5
XS GIS Cut Line= 3
2200102.65063188739319.4277637912199616.11150461739173.195224612
2199492.44571531739203.886004439
#Sta/Elev= 30
       0 1452.42    58.4 1438.93    77.8 1435.21    87.3 1434.17    90.3 1433.34
    94.5  1430.1    98.7 1428.69   111.2 1428.43   127.9 1425.18   161.3 1421.34
   190.5 1420.37   238.2    1420   392.4 1420.03   420.3 1419.48   470.4 1419.89
   474.6 1419.61  481.71 1415.97   482.9 1415.28   487.1 1415.12  491.16 1415.97
   498.4 1418.67   503.8 1419.72   532.7 1419.86   545.1 1422.92   565.7 1429.71
   582.2  1438.2   598.6 1447.59     607 1451.98   620.2 1455.74635.4568 1458.74
#Mann= 4 ,-1,0
       0     .07       0      70     .05       0  481.71    .045       0
  491.16     .05       0
#XS Ineff= 2 , 0
          298.35 1424.15
Permanent Ineff=
       F       F
Bank Sta=481.71,491.16
XS Rating Curve= 0 ,0
Exp/Cntr(USF)=0,0
Exp/Cntr=0.3,0.1

Type RM Length L Ch R = 1 ,9424    ,423.7,426.1,426.5
XS GIS Cut Line= 3
2200098.13728191739277.0022740292199611.59815464 739130.76973485
2199487.93236533739161.460514677
#Sta/Elev= 30
       0 1443.43    14.6 1440.69    27.1 1439.54    39.6 1437.08    56.3 1434.92
    73.1  1431.7    81.4 1427.89    98.1 1427.22   106.5  1425.2     119 1423.32
   144.1  1420.9   219.2  1419.6   445.1 1419.56   457.3 1418.86  463.43 1416.73
   467.1 1415.42   469.8 1415.43   471.9 1416.73     474 1418.12   478.2  1419.3
   499.1 1418.94   528.1 1419.46   536.3 1419.96   540.4 1420.87   569.3 1429.75
   584.5 1436.41   602.2 1445.67   610.5 1448.72   622.8 1452.24635.4568 1454.87
#Mann= 4 ,-1,0
       0     .07       0      70     .05       0  463.43    .045       0
   471.9     .05       0
#XS Ineff= 2 , 0
          299.12  1423.6
Permanent Ineff=
       F       F
Bank Sta=463.43,471.9
XS Rating Curve= 0 ,0
Exp/Cntr(USF)=0,0
Exp/Cntr=0.3,0.1

Type RM Length L Ch R = 1 ,8997    ,480,479.3,477.4
XS GIS Cut Line= 6
2200352.78490075 739005.968243422199935.51473792 738833.35769625
2199844.35743992738789.9863919172199632.28207667738620.795129254
2199543.92792268738566.0153831692199449.03703634738517.980046168
#Sta/Elev= 30
       0 1465.89    26.6 1461.63    56.9 1453.44    61.3    1452    69.9 1445.16
      96 1444.46   147.8 1439.94   182.5 1426.22   191.1 1424.11   247.4 1424.25
   290.7 1422.45   303.7 1422.93     390 1418.56   490.7 1418.74  497.45 1415.85
   499.6 1414.94  506.45 1415.85   514.2 1418.55   543.9 1418.89   550.3 1420.29
     573 1432.97   615.9 1454.22   638.7 1464.61     687 1479.58   748.2 1504.66
     797 1519.49   815.1  1522.7   858.5 1527.76   913.4 1530.611034.178 1534.42
#Mann= 7 ,-1,0
       0      .1       0      30     .06       0  138.44     .07       0
  245.31     .05       0  497.45    .045       0  506.45     .05       0
  562.51      .1       0
Bank Sta=497.45,506.45
XS Rating Curve= 0 ,0
Exp/Cntr(USF)=0,0
Exp/Cntr=0.3,0.1

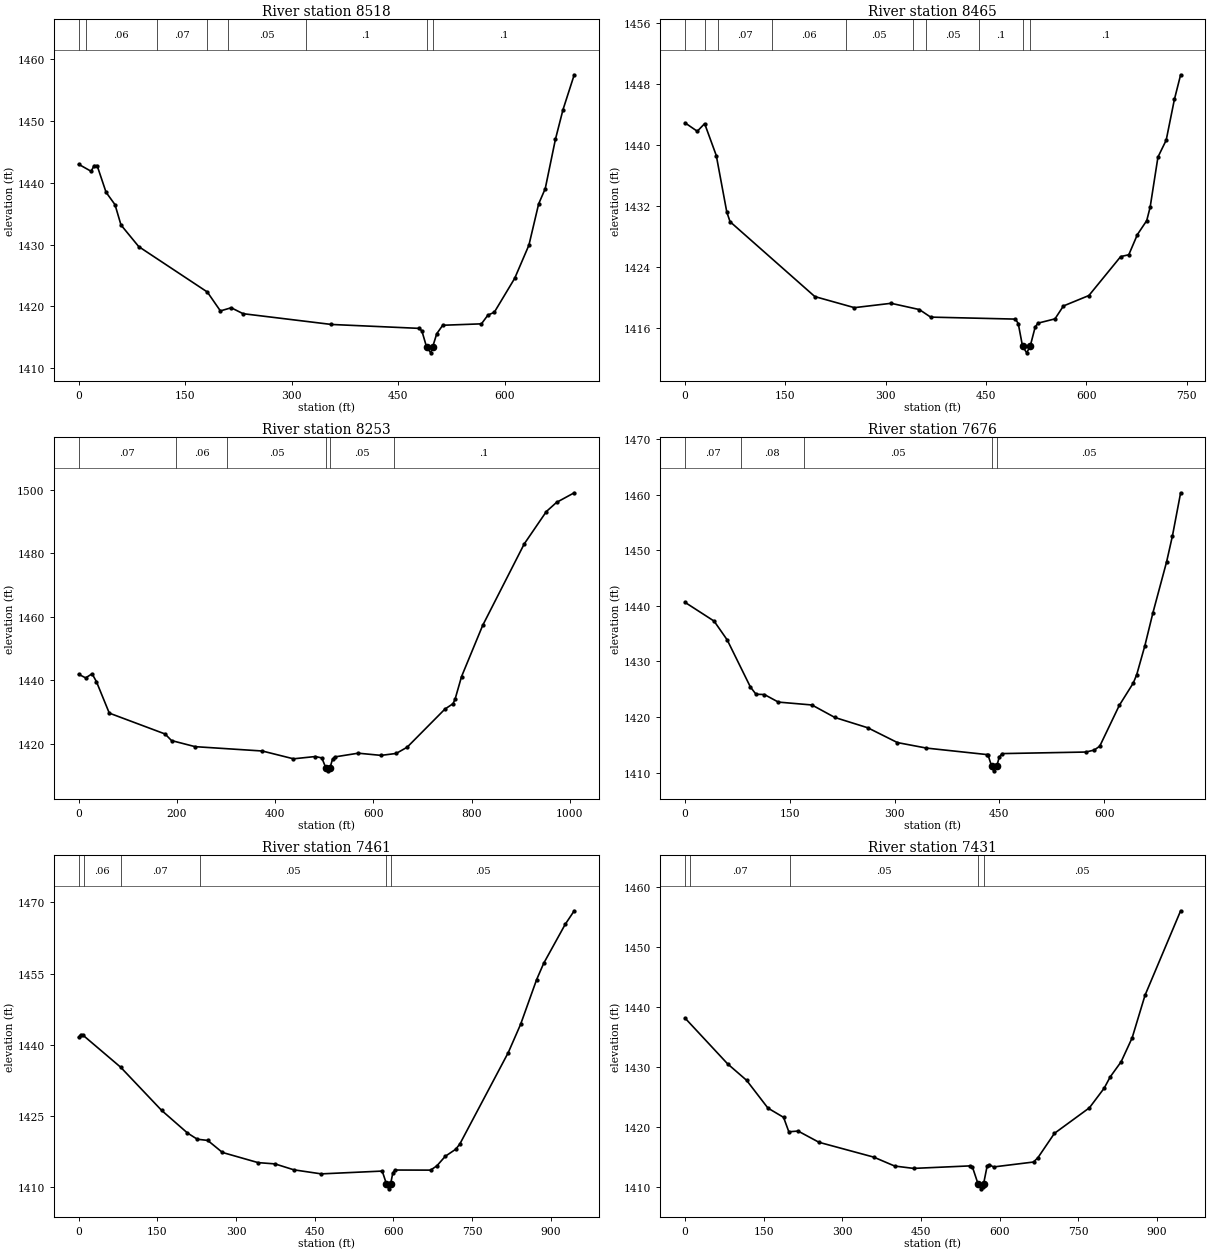
Type RM Length L Ch R = 1 ,8518    ,53.5,53.5,54.4
XS GIS Cut Line= 3
2200432.99808664738498.4431927112199875.79438606 738323.48123073
2199783.29857176738389.231267398
#Sta/Elev= 30
       0 1442.98    17.6 1441.84    21.8 1442.76      26 1442.77    38.6 1438.45
    51.2 1436.44    59.6 1433.16    84.6 1429.66   181.1 1422.32   199.5 1419.26
   214.7 1419.77   231.5 1418.81   355.8 1417.07   478.8 1416.44     483 1416.06
   489.7 1413.42   495.6 1412.48   498.2 1413.42     504 1415.57   512.4 1416.94
   566.9 1417.17     576 1418.58     585 1419.04   613.7 1424.53   633.7 1429.89
   647.4 1436.56   656.7 1439.04     671    1447   681.7 1451.81   697.5 1457.45
#Mann= 8 ,-1,0
       0     .03       0      10     .06       0     110     .07       0
     180     .06       0     210     .05       0     320      .1       0
   489.7    .045       0   498.2      .1       0
Bank Sta=489.7,498.2
XS Rating Curve= 0 ,0
Exp/Cntr(USF)=0,0
Exp/Cntr=0.3,0.1

Type RM Length L Ch R = 1 ,8465    ,210.3,211.4,212
XS GIS Cut Line= 3
2200451.94301246738460.5533410722199884.70964527738268.875268073
2199753.20957193738322.366823329
#Sta/Elev= 30
       0 1442.88    18.3 1441.78    29.3 1442.78    46.7  1438.6    62.4  1431.2
    67.3 1429.93     194 1420.12   253.1 1418.67     308 1419.24   350.2 1418.42
   367.1 1417.43   493.8 1417.17     498 1416.59   504.4 1413.62   510.6 1412.75
  515.87 1413.62   523.3 1416.13   527.5 1416.64   552.9  1417.2   565.5 1418.89
   603.6 1420.26   651.1 1425.36   663.2  1425.6   676.1 1428.25     690 1430.07
   695.1 1431.82   706.8  1438.4   719.1 1440.61   731.4 1445.96   740.7 1449.18
#Mann= 10 ,-1,0
       0     .03       0      30     .06       0      50     .07       0
     130     .06       0     240     .05       0     340      .1       0
     360     .05       0     440      .1       0   504.4    .045       0
  515.87      .1       0
Bank Sta=504.4,515.87
XS Rating Curve= 0 ,0
Exp/Cntr(USF)=0,0
Exp/Cntr=0.3,0.1

Type RM Length L Ch R = 1 ,8253    ,579.6,577.3,572.8
XS GIS Cut Line= 6
2200505.22225992738314.7950850872200237.63585284738197.181803256
2200157.90208842738158.6897542632200091.23161809738122.401769087
2199999.04905967738081.7092651722199578.54399517737917.331641167
#Sta/Elev= 30
       0 1441.89    14.3 1440.75    27.4 1442.04    36.2 1439.58    62.4 1429.65
     176 1423.07   189.1    1421   237.1 1419.08   373.9 1417.71   437.4 1415.25
   481.9 1415.97   495.1 1415.53  503.18 1412.45   508.2 1411.46  511.84 1412.45
   516.9 1415.14   521.3 1415.84   569.2 1417.02   615.7 1416.33   646.5 1416.94
   668.8  1418.9   745.7 1430.91   762.4 1432.64   766.7  1434.2   779.6 1441.17
   822.6 1457.28   907.1 1482.93   952.3 1493.17   972.9 1496.031008.996 1499.07
#Mann= 6 ,-1,0
       0     .07       0  197.53     .06       0  302.29     .05       0
  503.18    .045       0  511.84     .05       0   642.5      .1       0
Bank Sta=503.18,511.84
XS Rating Curve= 0 ,0
Exp/Cntr(USF)=0,0
Exp/Cntr=0.3,0.1

Type RM Length L Ch R = 1 ,7676    ,214.1,214.6,214.5
XS GIS Cut Line= 2
2200697.76538688737596.1232653952199988.45806983737576.250431081
#Sta/Elev= 30
       0 1440.62    41.6 1437.25    60.4 1433.86    93.6  1425.4   101.6  1424.1
   113.6 1424.05   133.6 1422.69   181.7 1422.17   214.6 1419.92   261.7 1418.07
   304.1 1415.41   345.7 1414.42   432.6 1413.25   433.8 1413.18   439.1 1411.12
   441.8 1410.33  446.18 1411.12   449.8 1412.76   453.8 1413.43   573.8 1413.71
   585.8 1414.06   593.8 1414.77   621.8 1422.11   641.8 1426.12   646.7 1427.62
   658.4 1432.84     670 1438.79   689.5 1447.91   697.9  1452.6709.5856 1460.32
#Mann= 5 ,-1,0
       0     .07       0      80     .08       0     170     .05       0
   439.1    .045       0  446.18     .05       0
Bank Sta=439.1,446.18
XS Rating Curve= 0 ,0
Exp/Cntr(USF)=0,0
Exp/Cntr=0.3,0.1

Type RM Length L Ch R = 1 ,7461    ,30.4,30.3,30.3
XS GIS Cut Line= 6
2200827.63325363737492.4523809792200638.87881595737397.182964571
2200544.93051303737391.8217548212200282.22828253737373.522250735
2200119.95170421737365.2184615662199933.78156827737470.092300073
#Sta/Elev= 30
       0 1441.59     3.9 1442.15     8.4 1442.01      80 1435.29   158.2 1426.19
   207.5 1421.43   226.2 1420.12   246.2 1419.86   274.2 1417.33   342.2 1415.19
   374.5 1414.92   410.5 1413.67   462.7 1412.82   578.9 1413.41     587  1410.7
     591 1409.67  594.91  1410.7     599 1412.97     603 1413.63   671.1 1413.61
   683.1 1414.51   699.1 1416.52   719.1 1418.01   726.9 1419.11   819.3 1438.37
   842.8 1444.31   873.4 1453.74   886.8 1457.15   927.9 1465.37945.0428 1468.21
#Mann= 6 ,-1,0
       0     .07       0      10     .06       0      80     .07       0
  231.43     .05       0     587    .045       0  594.91     .05       0
Bank Sta=587,594.91
XS Rating Curve= 0 ,0
Exp/Cntr(USF)=0,0
Exp/Cntr=0.3,0.1

Type RM Length L Ch R = 1 ,7431    ,213.2,214.7,214.9
XS GIS Cut Line= 6
2200804.88104959737460.9002883522200616.12661191737365.630871944
2200522.17830898737360.2696621932200259.47607849737341.970158107
2200097.19950016737333.6663689382199911.02936423737438.540207446
#Sta/Elev= 30
       0 1438.14    81.4 1430.51   117.3  1427.8   158.1 1423.17   187.9 1421.63
   197.9 1419.23   215.6 1419.35   255.5 1417.48   359.7 1415.02   399.8 1413.53
   435.9 1413.14   544.1 1413.56   548.1 1413.35   558.7 1410.57   564.2 1409.74
   568.2  1410.1  569.28 1410.57   576.2 1413.59   580.2 1413.76   588.2 1413.38
   664.5  1414.2   672.9 1414.92   704.4 1418.97   771.1 1423.22   799.3 1426.49
   810.6 1428.34   831.6 1430.88   852.6 1434.86   877.1 1441.93945.0428 1455.99
#Mann= 5 ,-1,0
       0     .06       0      10     .07       0     200     .05       0
   558.7    .045       0  569.28     .05       0
Bank Sta=558.7,569.28
XS Rating Curve= 0 ,0
Exp/Cntr(USF)=0,0
Exp/Cntr=0.3,0.1

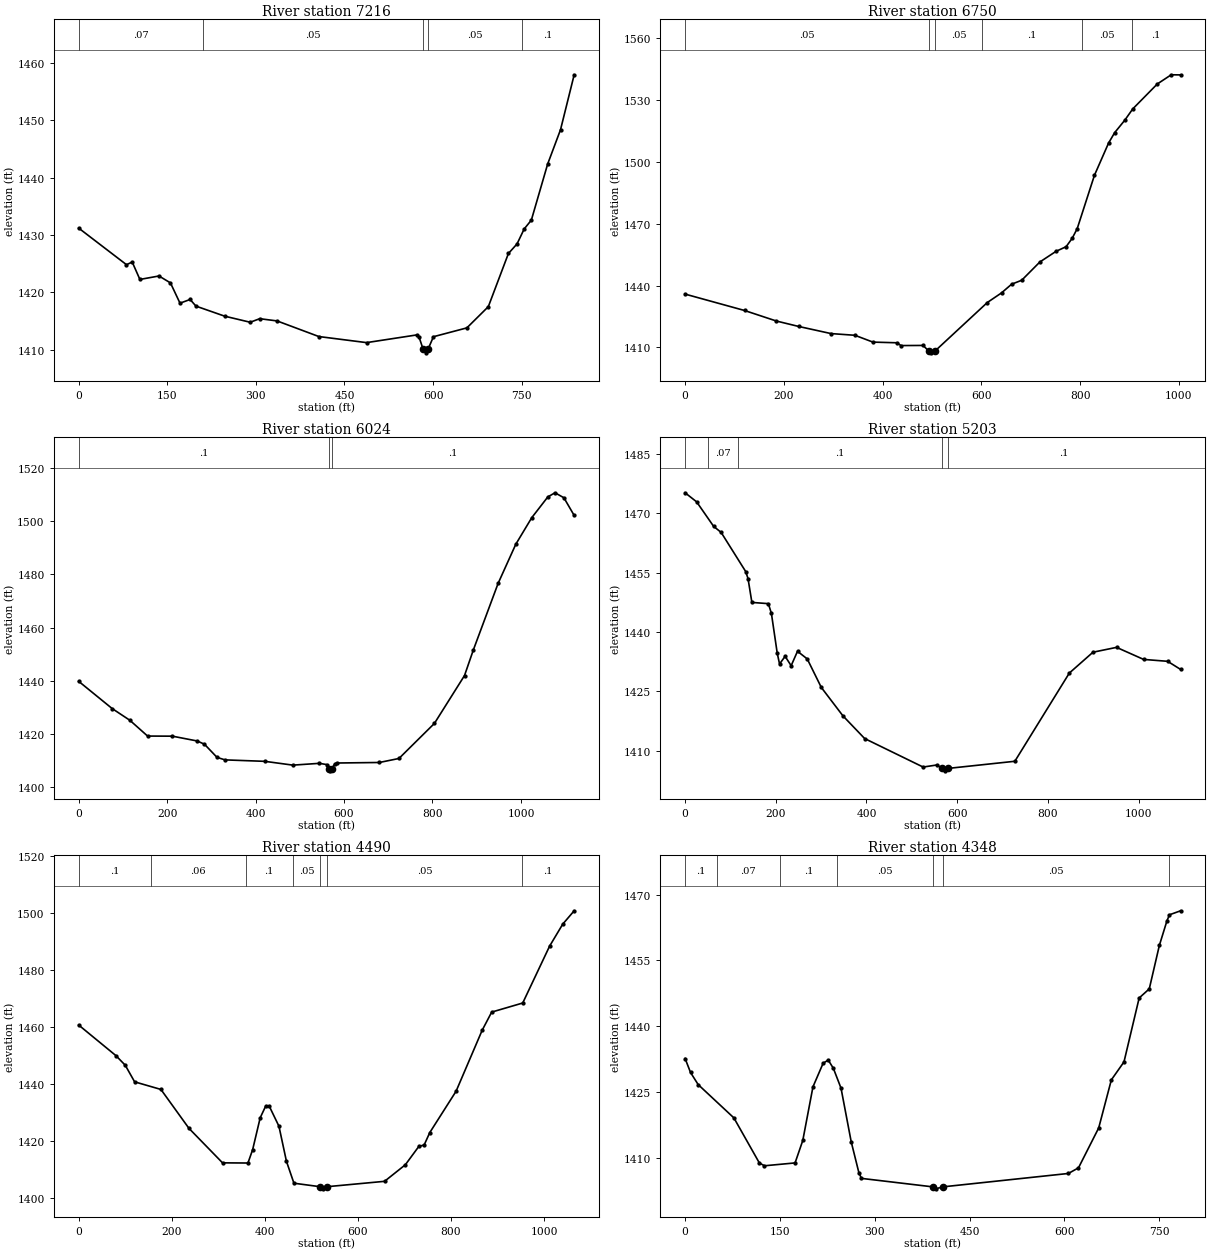
Type RM Length L Ch R = 1 ,7216    ,469.9,466.3,462.9
XS GIS Cut Line= 3
2200783.37144239737400.4522813782200523.49591675737165.035628734
2200040.43317495737094.716368853
#Sta/Elev= 30
       0 1431.21      81 1424.83    90.7 1425.29   103.7 1422.26     136 1422.86
   155.4 1421.66   171.6 1418.12   188.7 1418.77   198.6 1417.61   247.2 1415.86
   290.4  1414.8   306.6 1415.42   335.9 1415.03   406.6 1412.31   487.4 1411.25
   572.3 1412.59   576.3  1412.2   582.8  1410.2   588.5 1409.47  591.84  1410.2
   600.6 1412.28   657.2 1413.82   693.5 1417.52   727.5 1426.78   742.1 1428.45
   754.2 1431.06   766.3 1432.59   793.9 1442.36   815.7 1448.35838.8053 1457.92
#Mann= 5 ,-1,0
       0     .07       0     210     .05       0   582.8    .045       0
  591.84     .05       0  750.65      .1       0
Bank Sta=582.8,591.84
XS Rating Curve= 0 ,0
Exp/Cntr(USF)=0,0
Exp/Cntr=0.3,0.1

Type RM Length L Ch R = 1 ,6750    ,712.1,726.1,729.5
XS GIS Cut Line= 6
2200822.80036493736585.6817454252200279.54390551736681.041790918
2200206.04077168736696.1037686772200120.42545734736714.460687339
2199933.86086984736754.6807512492199837.54446143736775.675131842
#Sta/Elev= 30
       0 1435.89   120.4 1427.93   184.9 1422.82   230.1 1420.18   295.5 1416.73
   343.9  1415.9   380.4 1412.59   429.1 1412.26   437.2 1410.91   481.9 1410.97
  493.63 1408.24   498.1 1407.38  506.04 1408.24   612.1 1431.81   640.8 1436.47
   661.2 1440.68   681.7 1442.61   718.5 1451.48   751.2 1456.64   771.7 1458.91
     784    1463   794.1 1467.65     829 1493.55   857.6 1509.18   869.9 1514.23
   890.4 1520.27   906.7  1525.8   956.3 1537.87   984.5 1542.341003.583 1542.28
#Mann= 6 ,-1,0
       0     .05       0  493.63    .045       0  506.04     .05       0
  601.56      .1       0  804.15     .05       0     905      .1       0
Bank Sta=493.63,506.04
XS Rating Curve= 0 ,0
Exp/Cntr(USF)=0,0
Exp/Cntr=0.3,0.1

Type RM Length L Ch R = 1 ,6024    ,825.9,820.9,803.6
XS GIS Cut Line= 6
2200751.94748826736236.911117509  2200544.639832736228.256607249
2200347.63136776736191.4121927622200190.80720635736061.943619668
2199895.90458092736039.7832309162199685.16943809736056.196255833
#Sta/Elev= 30
       0 1439.74    75.8 1429.46   115.8 1425.04   155.9 1419.09     212 1419.05
   268.2 1417.23   284.5 1416.01   312.8 1411.07   330.9 1410.11   421.1 1409.56
   484.4 1408.13   544.4 1408.81   561.2 1408.33  565.65 1406.75   567.5 1405.98
   572.5 1406.75     579 1408.59   583.8 1408.93   679.9 1409.13   724.2 1410.64
   804.4 1423.87   872.4  1441.9   892.4 1451.57   948.4 1476.66   988.4 1491.42
  1024.5 1501.43  1060.8 1509.25    1077  1510.8  1097.1 1508.921120.317 1502.26
#Mann= 3 ,-1,0
       0      .1       0  565.65    .045       0   572.5      .1       0
Bank Sta=565.65,572.5
XS Rating Curve= 0 ,0
Exp/Cntr(USF)=0,0
Exp/Cntr=0.3,0.1

Type RM Length L Ch R = 1 ,5203    ,700.8,713.2,714.1
XS GIS Cut Line= 6
2200576.63090976735362.1028277582200474.33091751735391.275341585
2200283.03766492735473.9782601742200202.76420343735528.958137095
2200056.46167451735655.2692361772199571.78383809735692.867914259
#Sta/Elev= 30
       0 1475.22    25.4 1472.93    62.9 1466.73    79.5 1465.19   133.6  1455.3
   138.8 1453.51   147.3 1447.48   183.6 1447.17   190.3 1444.73   203.2 1434.64
   208.3 1431.91   220.6 1433.84   233.9 1431.47   247.9 1435.12   269.4 1433.18
   300.4 1425.97   348.1 1418.78     396 1413.04   524.9 1405.83   555.2 1406.35
   567.2 1405.48   573.6 1404.87   579.5 1405.48   727.2 1407.29   847.4 1429.61
   899.5 1434.88   951.5 1436.11  1011.2 1433.06  1064.2 1432.581092.867 1430.52
#Mann= 5 ,-1,0
       0     .06       0      50     .07       0  116.38      .1       0
   567.2    .045       0   579.5      .1       0
Bank Sta=567.2,579.5
XS Rating Curve= 0 ,0
Exp/Cntr(USF)=0,0
Exp/Cntr=0.3,0.1

Type RM Length L Ch R = 1 ,4490    ,125.7,141.5,151.6
XS GIS Cut Line= 6
2200582.87531984735137.3175161782200375.76746634735106.782472253
2200275.96550059 735106.201108592200108.56918184735129.409395501
2199924.53871001735078.9124492562199531.91777609 735031.72422342
#Sta/Elev= 30
       0 1460.66    79.9 1449.97   100.2 1446.57   120.3 1440.76   176.8  1438.1
     237 1424.49   309.2  1412.4   363.8 1412.34   373.9 1417.02   390.1 1428.17
   402.2 1432.37   409.5 1432.27   430.4 1425.22   446.5 1412.95   462.6 1405.27
  519.24 1404.04   524.8  1403.3     533 1404.04   657.3 1405.93     702 1411.73
     731 1418.16   742.4 1418.65   754.5    1423     811 1437.47     867  1458.8
   887.5 1465.18   954.2 1468.36    1012 1488.29  1040.3    14961064.738 1500.65
#Mann= 7 ,-1,0
       0      .1       0  155.22     .06       0  359.22      .1       0
  459.63     .05       0  519.24    .045       0     533     .05       0
  953.34      .1       0
Bank Sta=519.24,533
XS Rating Curve= 0 ,0
Exp/Cntr(USF)=0,0
Exp/Cntr=0.3,0.1

Type RM Length L Ch R = 1 ,4348    ,128.8,118.6,116.3
XS GIS Cut Line= 4
2200372.65112849735040.0380577412200091.92076006735077.950197529
2199953.41106417734855.7930821082199714.60470218734864.017408729
#Sta/Elev= 30
       0 1432.68     8.6  1429.5    20.7 1426.74    77.2 1419.16   117.5  1408.9
   125.6 1408.26     174 1408.91   186.2 1414.02   202.3 1426.23   218.4 1431.61
   226.5 1432.32   234.6 1430.44   246.7 1425.93   262.8 1413.73   274.9 1406.72
     279 1405.39  391.98 1403.46   396.2 1403.01  407.73 1403.46   606.4 1406.51
   622.4 1407.79   654.4 1416.88   674.4 1427.82   694.4 1431.91   718.4 1446.46
   734.4 1448.53   750.4 1458.45   762.4 1464.04   766.4  1465.4784.0258 1466.31
#Mann= 7 ,-1,0
       0      .1       0      50     .07       0     150      .1       0
     240     .05       0  391.98    .045       0  407.73     .05       0
  765.08      .1       0
Bank Sta=391.98,407.73
XS Rating Curve= 0 ,0
Exp/Cntr(USF)=0,0
Exp/Cntr=0.3,0.1