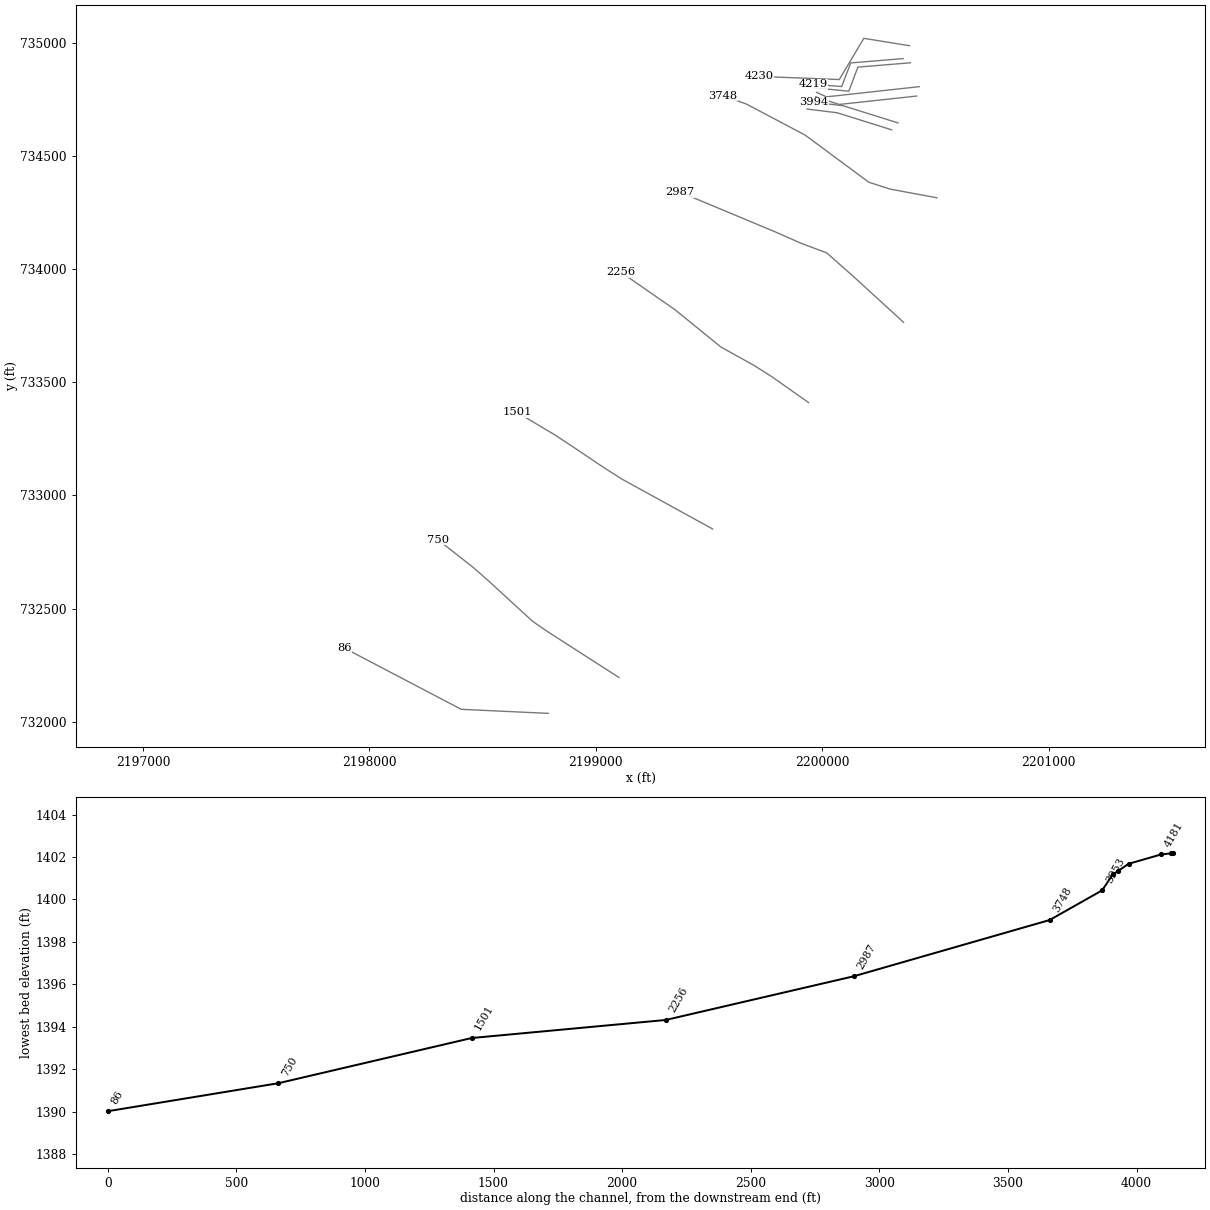
HEC-RAS study BRUSHRN2.prj: BRUSHRN2

--- BRUSHRN2.g01 (geometry) --- (continued)

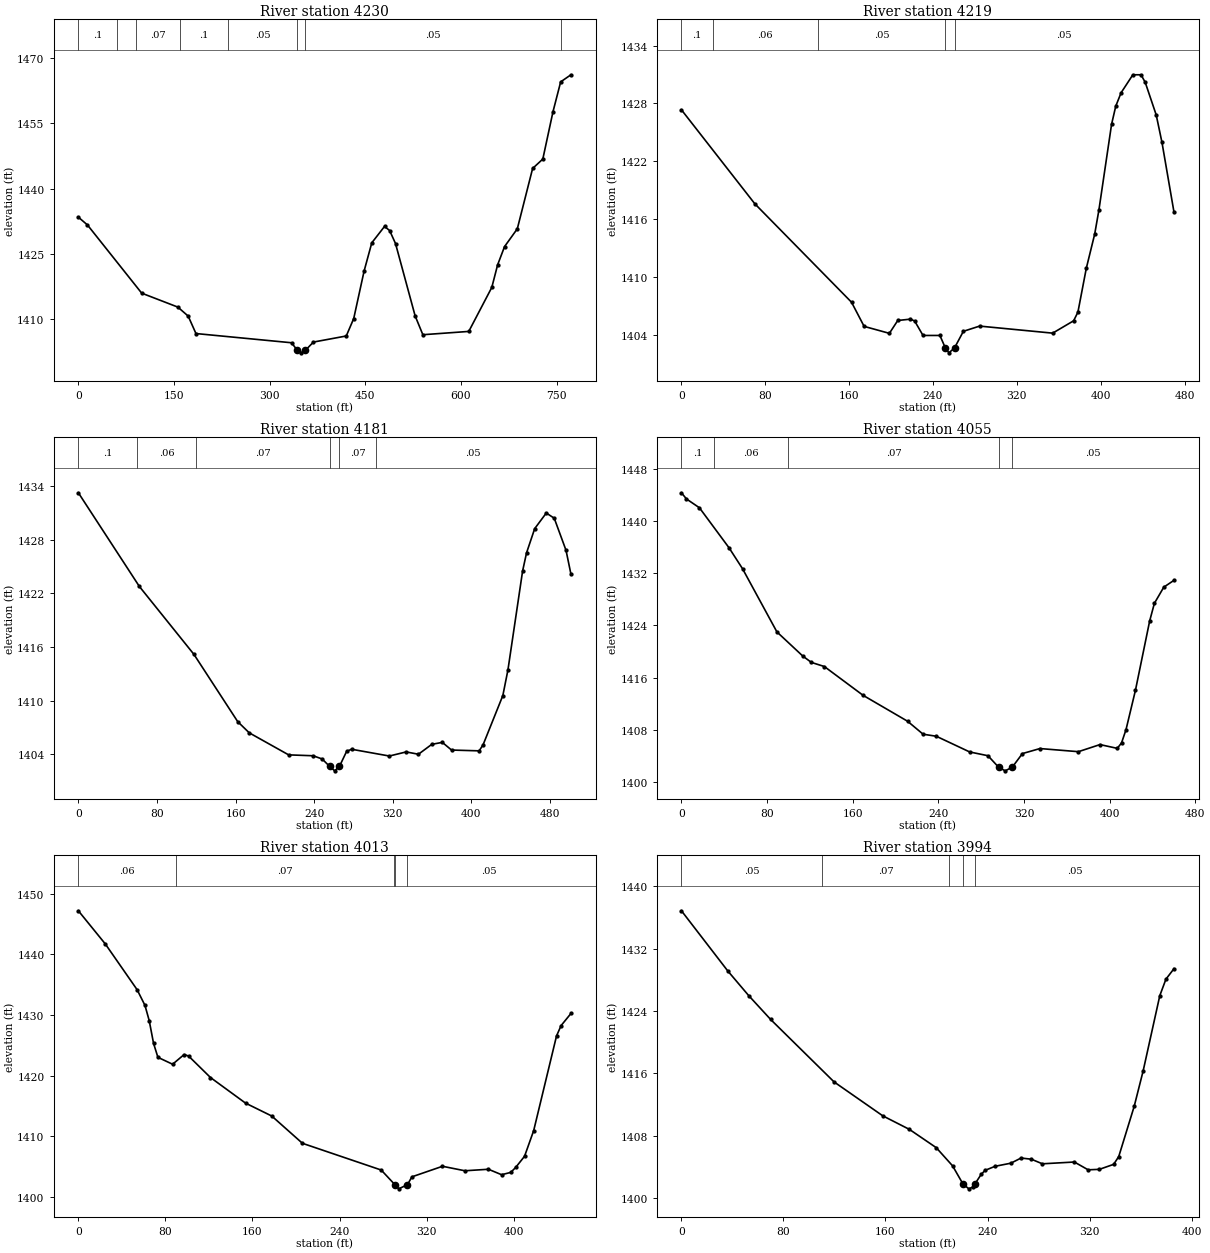
Type RM Length L Ch R = 1 ,4230    ,8.7,10.8,11.6
XS GIS Cut Line= 4
2200386.19117841734986.3291930432200183.99309955735018.925609527
2200075.57240349734836.8871605482199720.12101881734850.828397136
#Sta/Elev= 30
       0  1433.4    14.2 1431.62    99.3 1415.91     156  1412.7   172.2 1410.63
   184.4 1406.61   334.3 1404.49  343.51 1402.72   348.9 1402.17   355.8 1402.72
   368.6 1404.65   420.1 1406.05   431.8 1410.07   448.1 1421.02   460.1 1427.49
   480.1 1431.27   488.1 1430.32   497.3 1427.34   528.1 1410.67   540.2 1406.34
   612.2  1407.1   648.3 1417.23   657.4 1422.41   668.3 1426.63   688.3 1430.72
   712.3 1444.61   728.3 1446.78   744.3 1457.71   756.3 1464.55   772.4 1466.18
#Mann= 8 ,-1,0
       0      .1       0      60     .06       0      90     .07       0
     160      .1       0  234.81     .05       0  343.51    .045       0
   355.8     .05       0  756.69      .1       0
Bank Sta=343.51,355.8
XS Rating Curve= 0 ,0
Exp/Cntr(USF)=0,0
Exp/Cntr=0.3,0.1

Type RM Length L Ch R = 1 ,4219    ,37.8,37.4,38.1
XS GIS Cut Line= 4
2200357.90751857734929.4108350292200126.22221987734910.354468469
2200086.10355343734806.045935721 2199960.7327208734816.075602331
#Sta/Elev= 30
       0 1427.34      70 1417.61   162.3 1407.41   174.3 1404.91   198.4 1404.19
   206.4 1405.52   218.5 1405.66   222.5 1405.47   230.5 1403.97   246.6 1403.97
   251.8 1402.68   255.2 1402.17  260.55 1402.68     269  1404.4   284.5 1404.94
   354.2 1404.21   374.2 1405.49   378.3 1406.39   386.3 1410.93   394.3 1414.47
   398.3 1416.95   410.4 1425.84   414.4 1427.72   419.5 1429.11   430.7 1430.97
   438.5 1430.97   442.5 1430.19     453 1426.81   458.5 1423.96469.9967 1416.72
#Mann= 5 ,-1,0
       0      .1       0      30     .06       0     130     .05       0
   251.8    .045       0  260.55     .05       0
Bank Sta=251.8,260.55
XS Rating Curve= 0 ,0
Exp/Cntr(USF)=0,0
Exp/Cntr=0.3,0.1

Type RM Length L Ch R = 1 ,4181    ,132.1,126.1,119.3
XS GIS Cut Line= 4
2200389.50096839734910.8559517992200157.81566969 734891.79958524
2200117.69700325734785.4851191692199963.24013745734800.529619085
#Sta/Elev= 30
       0 1433.28    62.1 1422.78   117.7 1415.16   162.2 1407.63   173.9 1406.38
     214 1403.91   238.9 1403.81   248.1 1403.45  255.61 1402.63   260.9 1402.12
  265.76 1402.63     273  1404.3     278 1404.54   316.5 1403.78   333.6 1404.24
   346.1 1403.98   359.7 1405.09   370.4 1405.31   379.8 1404.45   407.9 1404.36
   411.9 1405.04     432 1410.56   437.2 1413.44   452.1 1424.51   456.1 1426.54
   464.4 1429.26   476.2 1431.01   484.3 1430.43   496.3 1426.83   501.3 1424.16
#Mann= 6 ,-1,0
       0      .1       0      60     .06       0     120     .07       0
  255.61    .045       0  265.76     .07       0  302.47     .05       0
Bank Sta=255.61,265.76
XS Rating Curve= 0 ,0
Exp/Cntr(USF)=0,0
Exp/Cntr=0.3,0.1

Type RM Length L Ch R = 1 ,4055    ,47.6,42,40.7
XS GIS Cut Line= 3
2200428.88751669734805.5667857882200018.67415232734760.433286041
 2199975.5465859734780.492619262
#Sta/Elev= 30
       0 1444.35     4.7  1443.4    16.8 1442.05    44.5  1435.9    57.1 1432.69
    89.2    1423   113.4 1419.29   121.4 1418.32   133.5 1417.69   169.7 1413.27
   211.3 1409.29   225.8  1407.3   238.1 1406.99   269.3 1404.58   286.4    1404
  296.33 1402.24   302.5 1401.68   309.1 1402.24   318.6 1404.33     335  1405.1
   370.9 1404.62   391.1 1405.71   407.2 1405.13   411.2 1405.96   415.4 1408.01
   424.2 1414.04   437.5 1424.69   441.9 1427.39   450.7 1429.87460.2531 1430.92
#Mann= 5 ,-1,0
       0      .1       0      30     .06       0     100     .07       0
  296.33    .045       0   309.1     .05       0
Bank Sta=296.33,309.1
XS Rating Curve= 0 ,0
Exp/Cntr(USF)=0,0
Exp/Cntr=0.3,0.1

Type RM Length L Ch R = 1 ,4013    ,23.8,19,15.5
XS GIS Cut Line= 3
2200416.85191676734763.9436693552200074.88040401734726.934199563
2199971.63501592734760.804383706
#Sta/Elev= 30
       0 1447.19    24.8 1441.71      54 1434.17    61.2 1431.59    65.1 1429.08
    69.1 1425.32    73.1 1423.02    86.6 1421.88    97.2 1423.48   101.3 1423.23
   121.4 1419.69   153.6 1415.47   177.7 1413.34   205.9 1408.84   278.3 1404.43
  290.84 1402.02   294.4 1401.33   302.4 1402.02   306.5 1403.31   334.6 1405.05
   355.2 1404.31   376.8 1404.56   388.9 1403.66   397.3 1404.04   401.8 1404.85
     410  1406.7   418.4 1410.94   439.4 1426.56   443.6 1428.26452.6274 1430.25
#Mann= 5 ,-1,0
       0     .06       0      90     .07       0     290     .05       0
  290.84    .045       0   302.4     .05       0
Bank Sta=290.84,302.4
XS Rating Curve= 0 ,0
Exp/Cntr(USF)=0,0
Exp/Cntr=0.3,0.1

Type RM Length L Ch R = 1 ,3994    ,41,41.7,42.7
XS GIS Cut Line= 3
2200334.83933288734645.4130693532200093.55564324734720.966547929
2199961.13395498734737.214607838
#Sta/Elev= 30
       0 1436.85    36.3 1429.14    52.8 1425.96    69.9 1422.92   119.7  1414.9
   157.9 1410.55   178.8 1408.81   199.8 1406.47   212.6 1404.14   220.8  1401.8
   225.4 1401.19   228.6 1401.44  230.07  1401.8     235 1403.04   238.1 1403.56
   245.9 1404.08   258.3 1404.48   266.3 1405.14   274.4 1404.99     283  1404.4
   308.1 1404.63   318.9 1403.63   327.7 1403.69   338.9 1404.33   342.9 1405.33
     355 1411.76     362 1416.29   375.1 1425.97   379.9 1428.08 386.251 1429.43
#Mann= 5 ,-1,0
       0     .05       0     110     .07       0     210     .05       0
   220.8    .045       0  230.07     .05       0
Bank Sta=220.8,230.07
XS Rating Curve= 0 ,0
Exp/Cntr(USF)=0,0
Exp/Cntr=0.3,0.1

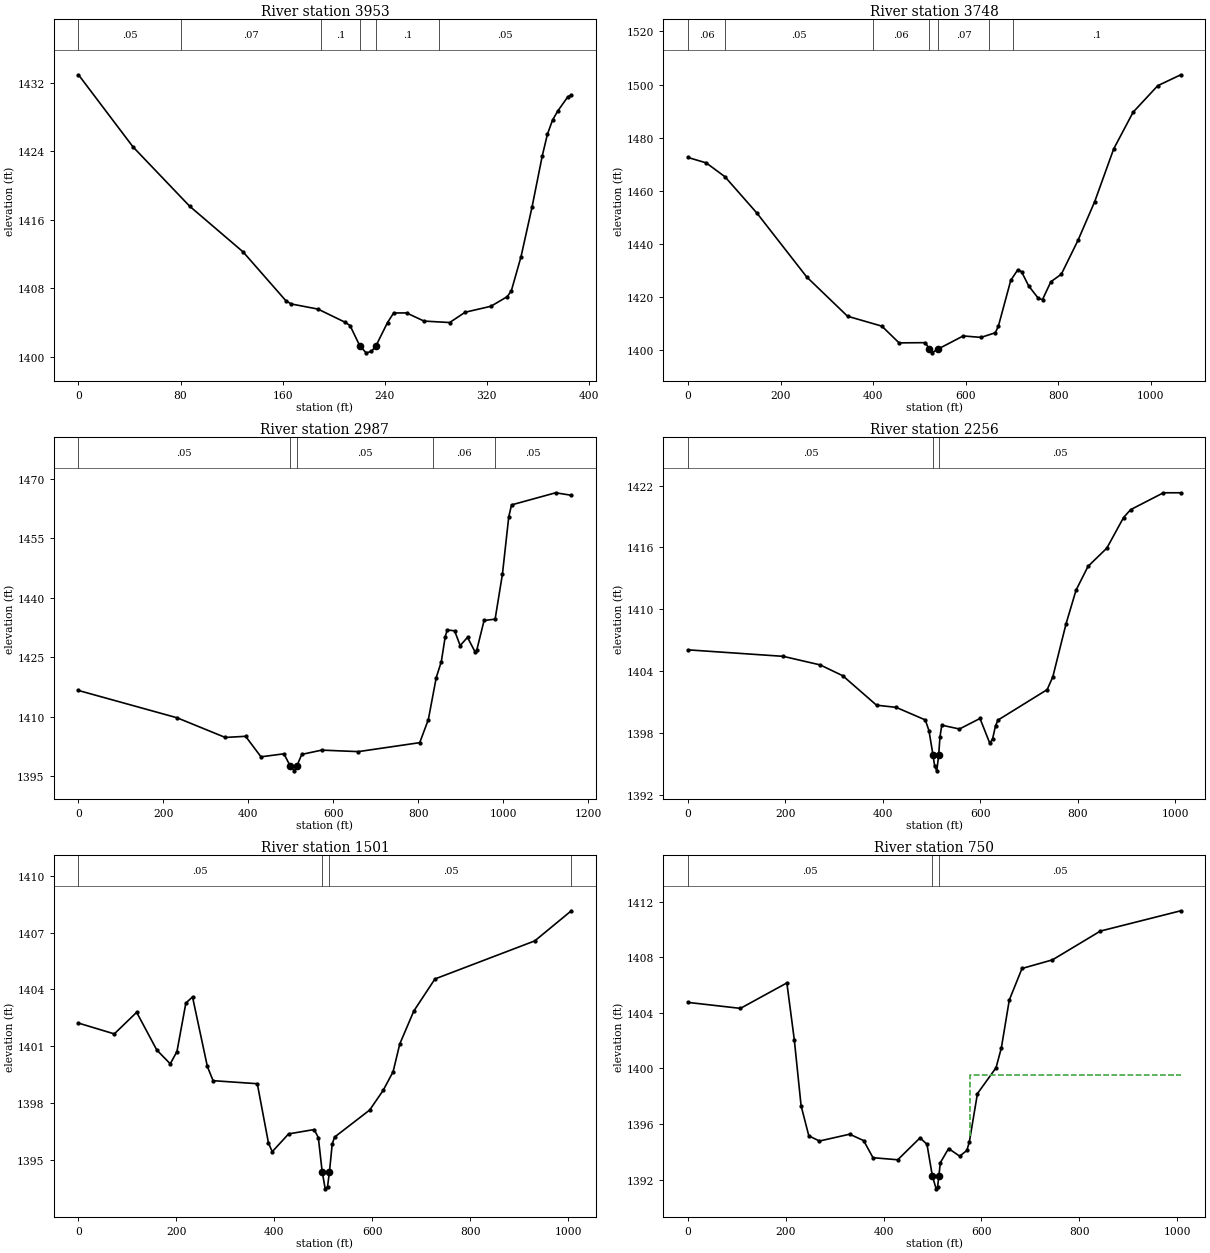
Type RM Length L Ch R = 1 ,3953    ,207.5,204.4,193.4
XS GIS Cut Line= 3
2200307.27566269734614.7091205732200065.99197304734690.262599149
2199933.57028478734706.510659058
#Sta/Elev= 30
       0 1432.91    42.7 1424.49    87.1 1417.56     129 1412.22   162.5 1406.52
   166.7 1406.14   187.7 1405.54   209.1 1403.99   212.8 1403.62   220.4 1401.27
   225.4 1400.43   229.6 1400.59   233.2 1401.27   242.2 1403.97     247 1405.09
   257.1 1405.09   270.8 1404.14   290.9 1403.97     303 1405.17   323.2 1405.87
   336.1    1407   339.3 1407.71   346.8 1411.65   355.4 1417.42   363.5 1423.46
   367.5 1425.96   371.5 1427.61   375.5 1428.65   383.6 1430.36 386.251 1430.54
#Mann= 6 ,-1,0
       0     .05       0      80     .07       0     190      .1       0
   220.4    .045       0   233.2      .1       0  282.84     .05       0
Bank Sta=220.4,233.2
XS Rating Curve= 0 ,0
Exp/Cntr(USF)=0,0
Exp/Cntr=0.3,0.1

Type RM Length L Ch R = 1 ,3748    ,745.1,761.3,758.9
XS GIS Cut Line= 6
2200507.00998601734314.6170618392200301.12325868734352.843363345
2200206.29995751734383.2025545842199924.23916993734591.967885092
2199665.45261401734728.5844097582199561.38523684734766.333021924
#Sta/Elev= 30
       0 1472.56    39.4 1470.53    79.9 1465.32   149.2 1451.59   256.6 1427.59
   344.8 1412.81   418.9 1409.08   456.2 1402.78     513 1402.86  521.62  1400.4
   527.2 1399.03   539.8  1400.4   594.8 1405.39   633.4 1404.84     664 1406.59
   670.6 1408.99   697.5 1426.33   712.5 1430.25   720.7 1429.59   736.1 1424.24
   757.1 1419.52   766.1 1419.09   784.1 1425.79   806.7 1428.62   842.8  1441.4
   878.9 1455.97   919.9  1475.8   961.8  1489.6    1015 1499.571064.785 1503.68
#Mann= 7 ,-1,0
       0     .06       0      80     .05       0  398.81     .06       0
  521.62    .045       0   539.8     .07       0  650.79     .05       0
  701.44      .1       0
Bank Sta=521.62,539.8
XS Rating Curve= 0 ,0
Exp/Cntr(USF)=0,0
Exp/Cntr=0.3,0.1

Type RM Length L Ch R = 1 ,2987    ,730,731.1,719.2
XS GIS Cut Line= 6
2200359.39413951733764.7172430012200144.40277159733961.397952005
2200020.30754735734071.2208950822199906.54760426734113.874353096
2199793.83293468734163.6216289252199370.77374142734340.208218008
#Sta/Elev= 30
       0 1416.62   232.2 1409.74   345.5 1404.79   393.4 1405.08   429.6 1399.91
   483.6 1400.67  497.89 1397.72   508.4 1396.38  514.49 1397.72   525.6 1400.52
   572.6  1401.6   658.7 1401.22   803.3 1403.48   823.6 1409.28   842.2 1419.86
   854.2 1423.92   863.4  1430.2   868.2 1431.88   885.5 1431.64   898.5 1427.93
   915.8    1430   933.8  1426.3   937.4  1426.7   954.8 1434.25   980.8 1434.59
   998.1 1445.98  1012.9 1460.35  1019.5 1463.37  1123.3 1466.42 1160.24 1465.79
#Mann= 5 ,-1,0
       0     .05       0  497.89    .045       0  514.49     .05       0
  834.47     .06       0  981.01     .05       0
Bank Sta=497.89,514.49
XS Rating Curve= 0 ,0
Exp/Cntr(USF)=0,0
Exp/Cntr=0.3,0.1

Type RM Length L Ch R = 1 ,2256    ,749.7,754.3,751.6
XS GIS Cut Line= 6
2199940.02063443733410.0857344272199778.10658817733524.119955167
2199697.65432125733575.1342888332199552.97121167733655.377238587
2199348.75081959733821.2236916722199110.54952434733986.343440175
#Sta/Elev= 30
       0 1406.06   195.5 1405.43   271.4  1404.6   317.8 1403.55   387.2 1400.69
   427.5 1400.48   487.3 1399.26   494.8 1398.23   503.3 1395.81   506.6 1394.75
   510.9 1394.32   514.7 1395.81   517.5 1397.65   521.2 1398.75   557.4 1398.38
   599.6  1399.4   619.7    1397   625.4 1397.41   631.6 1398.71   636.7 1399.25
   737.5  1402.2   749.1 1403.44   776.3 1408.59   796.8 1411.85   821.4 1414.16
     860 1415.93   894.4  1418.9   908.8 1419.66   976.2  1421.31011.815  1421.3
#Mann= 3 ,-1,0
       0     .05       0   503.3    .045       0   514.7     .05       0
Bank Sta=503.3,514.7
XS Rating Curve= 0 ,0
Exp/Cntr(USF)=0,0
Exp/Cntr=0.3,0.1

Type RM Length L Ch R = 1 ,1501    ,750.4,751.4,745.2
XS GIS Cut Line= 6
2199516.22062901732851.8273365052199118.17516525733070.682541832
2199033.68320826733124.2434583462198898.89706051733215.012305677
2198820.63343751733266.632609248  2198652.171176733366.904390335
#Sta/Elev= 30
       0 1402.22    73.1 1401.65   118.8 1402.79   159.9  1400.8   187.4 1400.07
   201.1 1400.72   219.3 1403.28   232.9  1403.6   263.2 1399.93   274.9 1399.18
   365.2 1399.02     388 1395.89   395.7 1395.43   429.1 1396.37   481.3  1396.6
   489.8 1396.18   497.7 1394.38   503.9 1393.47   508.7 1393.59   512.6 1394.38
   518.2 1395.83   522.9  1396.2   594.7 1397.63   622.3 1398.67   642.5 1399.65
   656.2 1401.12   684.9 1402.86     728 1404.55   931.9 1406.561006.586 1408.15
#Mann= 4 ,-1,0
       0     .05       0   497.7    .045       0   512.6     .05       0
 1006.59     .06       0
Bank Sta=497.7,512.6
XS Rating Curve= 0 ,0
Exp/Cntr(USF)=0,0
Exp/Cntr=0.3,0.1

Type RM Length L Ch R = 1 ,750     ,663.5,663.5,663.5
XS GIS Cut Line= 6
 2199102.5226375732195.8466930842198782.86087526732401.242607757
2198720.67661643732444.2881253362198527.26361743 732621.76414834
2198456.80870584732683.6455862522198302.55343692  732804.3668015
#Sta/Elev= 30
       0 1404.75   107.3 1404.32   202.3 1406.15   217.5 1402.06   231.4 1397.31
   247.2 1395.15     269 1394.78   330.7 1395.27   359.3 1394.81   378.4 1393.58
     429 1393.43   474.7 1395.01   488.8 1394.54  499.68 1392.29   507.5 1391.34
   510.4 1391.47   513.2 1392.29   516.1 1393.22     533 1394.24   555.6 1393.69
   570.3  1394.1   575.5 1394.73     592 1398.19     630 1400.05   640.9 1401.48
   657.1 1404.92   683.1 1407.19   745.4 1407.81   843.4 1409.881007.755 1411.34
#Mann= 3 ,-1,0
       0     .05       0  499.68    .045       0   513.2     .05       0
#XS Ineff= 2 , 0
                          577.53         1399.56
Permanent Ineff=
       F       F
Bank Sta=499.68,513.2
XS Rating Curve= 0 ,0
Exp/Cntr(USF)=0,0
Exp/Cntr=0.3,0.1

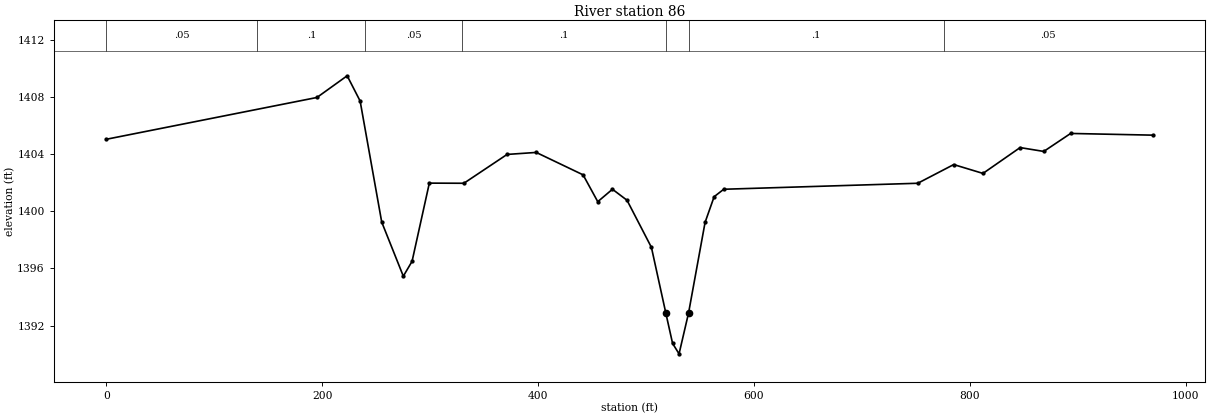
Type RM Length L Ch R = 1 ,86      ,,,
XS GIS Cut Line= 3
2198791.12117836732037.3989039142198405.89392857732055.284454797
2197888.58876458732326.319341252
#Sta/Elev= 30
       0 1405.05   195.2 1407.98   223.2  1409.5   235.2 1407.73   255.2 1399.25
   275.2 1395.46   283.3  1396.5   299.3 1401.98   331.3 1401.97   371.3 1403.99
   398.3 1404.13   441.7 1402.56   455.3 1400.68   468.9 1401.55   482.4 1400.78
     505 1397.48   518.3 1392.89   524.6 1390.75   530.6 1390.02   539.4 1392.88
   554.7 1399.23   563.1 1401.03     572 1401.55   751.7 1401.97     785 1403.28
   812.1 1402.66   846.5 1404.47   868.4  1404.2   893.3 1405.46969.6495 1405.34
#Mann= 7 ,-1,0
       0     .05       0     140      .1       0     240     .05       0
     330      .1       0   518.3    .045       0   539.4      .1       0
  775.64     .05       0
Bank Sta=518.3,539.4
XS Rating Curve= 0 ,0
Exp/Cntr(USF)=0,0
Exp/Cntr=0.3,0.1
LCMann Table=0

Chan Stop Cuts=-1
Use User Specified Reach Order=0
Composite Channel Slope=5